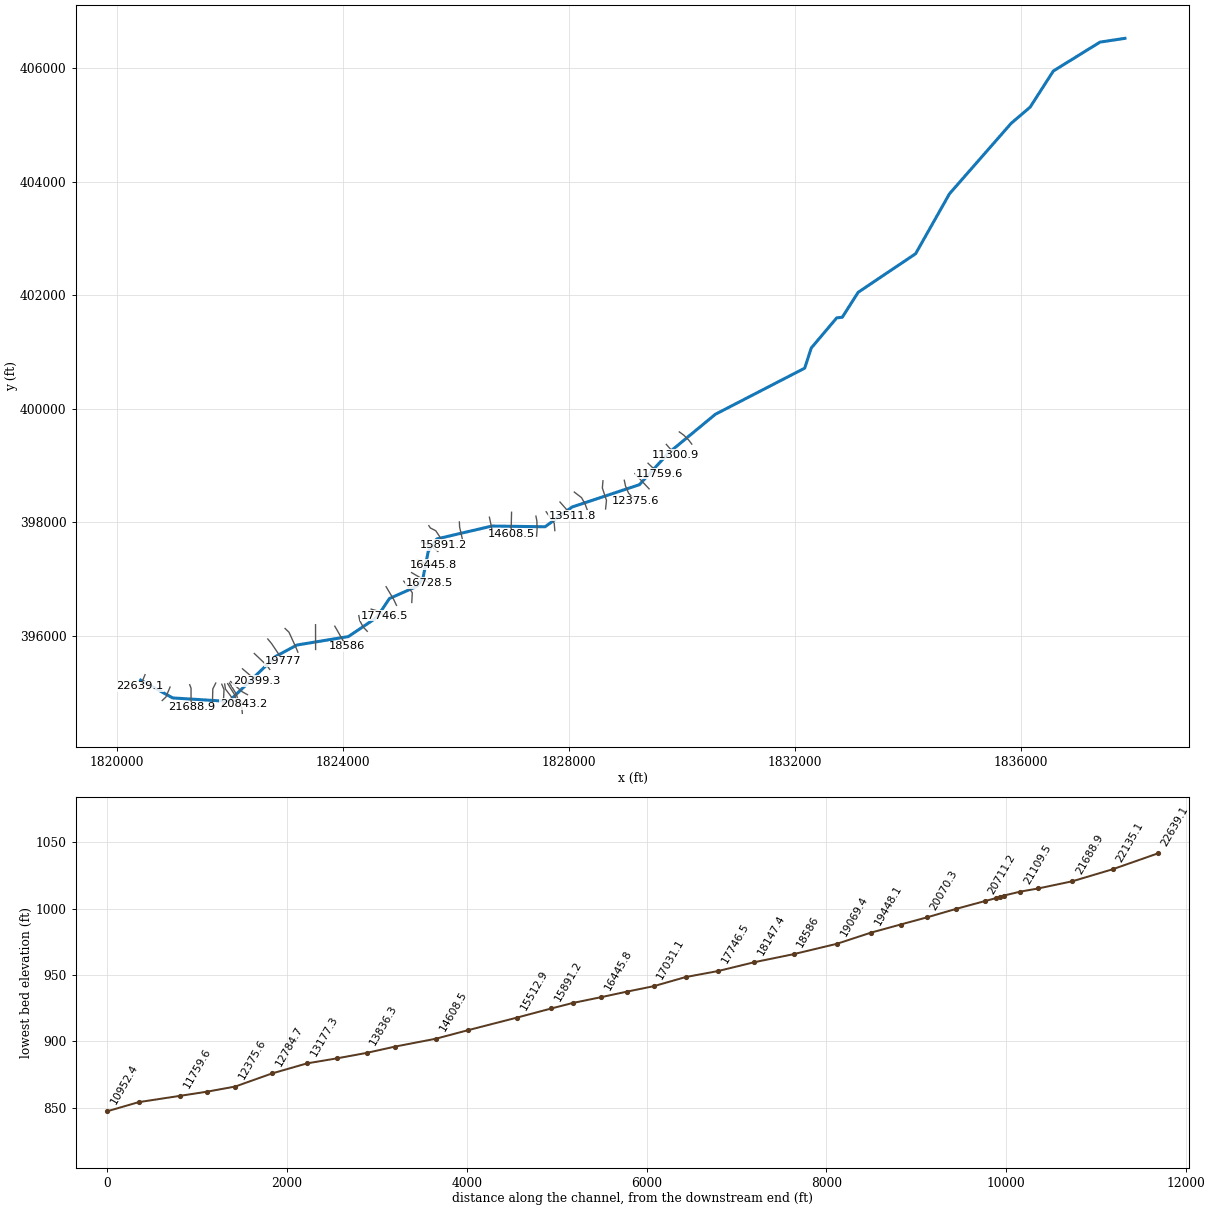
--- COALFORK.prj (project) ---

Proj Title=COALFORK
Current Plan=p01
Default Exp/Contr=0,0
English Units
Geom File=g01
Flow File=f01
Plan File=p01
BEGIN DESCRIPTION:
END DESCRIPTION:
DSS Export Rating Curves= 0
DSS Export Rating Curve Sorted= 0
DSS Export Volume Flow Curves= 0
DXF OffsetX= 0
DXF OffsetY= 0
DXF ScaleX= 0
DXF ScaleY= 0

--- COALFORK.p01 (plan) ---

Plan Title=Floodplain
Program Version=4.00
Geom File=g01
Flow File=f01
K Sum by GR=0
Std Step Tol=0.01
Critical Tol=0.01
Num of Std Step Trials=20
Max Error Tol=0.3
Flow Tol Ratio=0.001
Split Flow NTrial=30
Split Flow Tol=0.02
Split Flow Ratio=0.02
Log Output Level=0
Friction Slope Method=1
Unsteady Friction Slope Method=2
Unsteady Bridges Friction Slope Method=1
Global Log Level=0
CheckData=False
Run HTab=0
Run UNet=0
Run PostProcess=0
UNET Theta=0
UNET Theta Warmup=0
UNET ZTol=0
UNET ZSATol=0
UNET MxIter=0
UNET MaxInSteps=0
UNET DtIC=0
UNET DtMin=0
UNET MaxCRTS=0
UNET WFStab=0
UNET SFStab=0
UNET WFX=0
UNET SFX=0
UNET DSS MLevel=0
UNET DZMax Abort=0
UNET Convert EG Bridges=0
UNET Use Existing IB Tables=0
UNET Froude Limit=0
UNET Froude Power=0
Write IC File=0
Echo Input=False
Echo Output=False
Write Detailed=0

--- COALFORK.f01 (steady flow) ---

Flow Title=NFF Regression Equation
Program Version=4.10
Number of Profiles= 1
Profile Names=P100yr
River Rch & RM=COALFORK,Main            ,22639.1
974.9913
River Rch & RM=COALFORK,Main            ,21308.2
 1120.24
River Rch & RM=COALFORK,Main            ,20399.3
1400.482
River Rch & RM=COALFORK,Main            ,18147.4
1512.996
River Rch & RM=COALFORK,Main            ,16445.8
1594.804
River Rch & RM=COALFORK,Main            ,12784.7
1862.287
River Rch & RM=COALFORK,Main            ,8249.7
2791.082
River Rch & RM=COALFORK,Main            ,267.2
2979.383
Boundary for River Rch & Prof#=COALFORK,Main            , 1
Up Type= 0
Dn Type= 3
Dn Slope=0.008
DSS Import GetInterval= 0
DSS Import GetPeak= 0
DSS Import FillOption= 0

--- COALFORK.g01 (geometry) ---

Geom Title=USGS 10m DEM
Program Version=4.10

River Reach=COALFORK        ,Main
Reach XY= 30
     1820426.595      395218.225     1820992.478      394904.912
     1821986.401      394843.063     1822813.596      395634.695
     1823191.913      395836.986     1824102.287      395985.641
     1824605.759      396323.097     1824828.103      396655.263
      1825320.82      396873.227     1825422.816      397019.712
     1825515.571       397483.85     1825668.042      397705.476
     1826644.604      397932.255     1827583.189      397919.234
     1828060.997      398267.411     1829252.026      398660.337
     1829769.604      399221.318     1830596.427      399900.571
      1832176.59      400712.451     1832293.476      401068.106
     1832743.852      401598.663     1832842.087      401609.628
     1833123.337      402048.864     1834139.975      402728.045
     1834739.405      403784.759     1835830.394      405024.705
     1836166.884       405310.51     1836577.041      405946.361
     1837403.019      406455.014     1837844.402      406521.448

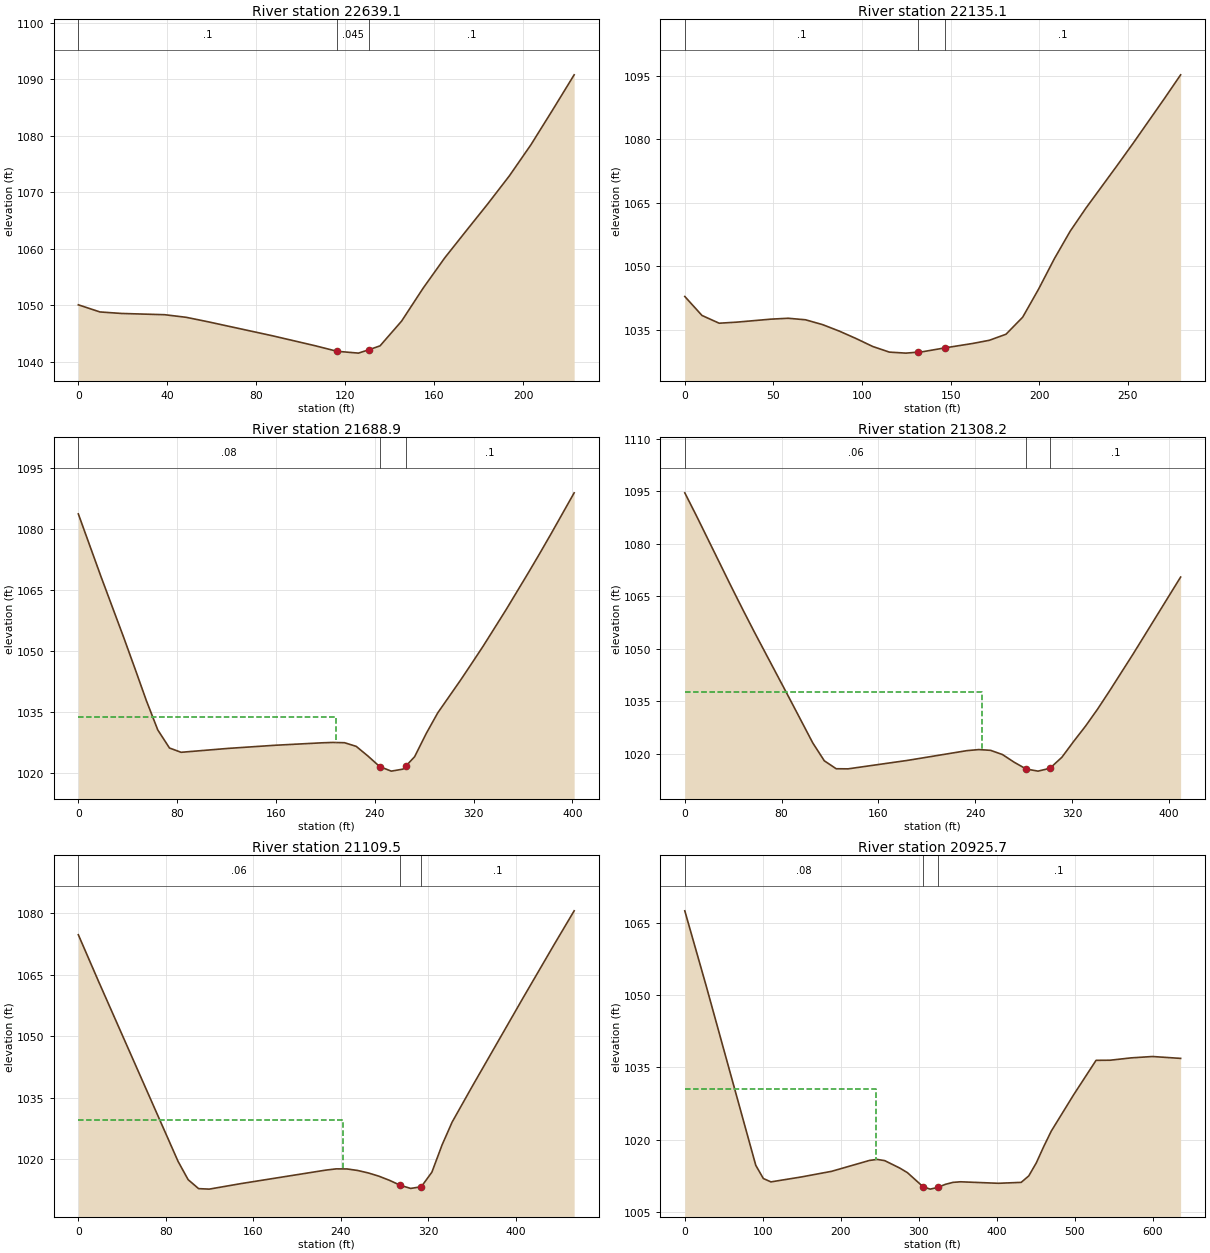
Type RM Length L Ch R = 1 ,22639.1 ,503.1,504.1,503.5
XS GIS Cut Line= 2
     1820503.926      395314.786     1820417.988      395109.056
#Sta/Elev= 27
       0 1050.07     9.7 1048.81    19.4 1048.54    29.1 1048.43    38.8 1048.32
    48.5 1047.86    58.2 1047.08    67.9 1046.25    77.6 1045.42    87.2  1044.6
    96.9 1043.71   106.6 1042.82   111.8  1042.3   116.3 1041.85     126 1041.52
   126.8 1041.63  130.87 1042.14   135.7 1042.81   145.4 1047.19   155.1 1053.03
   164.8 1058.38   174.5 1063.19   184.2 1067.96   193.9 1072.91   203.6 1078.42
   213.3 1084.54     223 1090.77
#Mann= 3 , 0 , 0
       0      .1       0   116.3    .045       0  130.87      .1       0
Bank Sta=116.3,130.87
XS Rating Curve= 0 ,0
Exp/Cntr=0.3,0.1

Type RM Length L Ch R = 1 ,22135.1 ,437.4,446.2,455.2
XS GIS Cut Line= 4
     1820946.634      395096.036     1820916.252      395024.421
     1820872.849      394920.254     1820807.745      394859.491
#Sta/Elev= 28
       0 1042.92     9.7 1038.44    19.4 1036.61    29.2 1036.86    48.6 1037.57
    58.3 1037.78    68.1 1037.42    77.8 1036.27    87.2 1034.74    96.6    1033
     106 1031.12   115.4 1029.79   124.8 1029.55   131.6 1029.79   134.2 1029.88
   146.6 1030.78   162.4 1031.83   171.8 1032.58   181.2 1034.01   190.6 1038.03
   199.6 1044.68   208.4 1051.78   217.4 1058.33   226.3 1063.79   244.1 1073.96
     253 1079.14   270.8 1089.79   279.7 1095.24
#Mann= 3 , 0 , 0
       0      .1       0   131.6    .045       0   146.6      .1       0
Bank Sta=131.6,146.6
XS Rating Curve= 0 ,0
Exp/Cntr=0.3,0.1

Type RM Length L Ch R = 1 ,21688.9 ,381.3,380.7,380.1
XS GIS Cut Line= 4
      1821294.29      395136.834     1821317.728      395076.938
     1821317.728      394859.491     1821334.655      394741.001
#Sta/Elev= 30
       0 1083.66    18.4 1068.24    36.8  1053.3    45.9 1045.67    55.1 1037.84
    64.3 1030.67    73.8 1026.22    83.2 1025.16     121 1026.11   158.9 1026.88
   196.7 1027.48   206.1 1027.58   215.6 1027.51     225 1026.62   234.5 1024.25
     244 1021.66   253.4 1020.54   262.9 1021.03     265 1021.71   272.3 1024.07
   281.8 1029.82     291 1034.82   309.4 1042.82   318.6 1046.99   327.8 1051.21
   346.2 1060.07   364.6 1069.32   373.8 1074.05     383 1078.89   401.5 1088.84
#Mann= 3 , 0 , 0
       0     .08       0     244    .045       0     265      .1       0
#XS Ineff= 2 , 0
          208.59 1033.93
Permanent Ineff=
       F       F
Bank Sta=244,265
XS Rating Curve= 0 ,0
Exp/Cntr=0.3,0.1

Type RM Length L Ch R = 1 ,21308.2 ,199,198.7,196.7
XS GIS Cut Line= 3
     1821755.228      395166.782     1821703.145      395063.918
     1821695.332      394769.647
#Sta/Elev= 26
       0 1094.54     9.6    1088    38.4 1067.77      48 1061.18    57.6 1054.73
    86.5 1035.87   105.7  1023.2   115.3 1018.06   125.1  1015.8   134.9 1015.77
     184 1018.18     233 1020.96   242.9 1021.27   252.7 1021.05   262.5 1019.85
   272.3 1017.63   282.1 1015.72   291.9 1015.12   301.7 1015.93   311.6 1019.08
   321.4 1023.64   331.2    1028     341 1032.77   350.8 1037.91   370.4 1048.52
   409.7  1070.5
#Mann= 3 , 0 , 0
       0     .06       0   282.1    .045       0   301.7      .1       0
#XS Ineff= 2 , 0
          245.79 1037.63
Permanent Ineff=
       F       F
Bank Sta=282.1,301.7
XS Rating Curve= 0 ,0
Exp/Cntr=0.3,0.1

Type RM Length L Ch R = 1 ,21109.5 ,167.9,183.8,201.2
XS GIS Cut Line= 4
     1821861.999      395145.949     1821901.061      395053.501
     1821890.645      394830.845      1821850.28      394707.147
#Sta/Elev= 25
       0 1074.75    18.2 1063.56    91.2 1019.51   100.4 1015.05     110 1012.86
   119.7 1012.74   148.8 1014.09   226.4 1017.38     236 1017.68   245.7 1017.66
   255.4 1017.29   265.1 1016.69   274.8  1015.9   284.5 1014.89   294.2  1013.7
   303.9 1012.91   313.3 1013.31   313.6 1013.32   323.3 1016.87   332.6  1023.5
   341.8 1029.07   360.4 1037.88   406.9 1059.46   434.8 1072.22   453.4 1080.58
#Mann= 3 , 0 , 0
       0     .06       0   294.2    .045       0   313.3      .1       0
#XS Ineff= 2 , 0
          241.81 1029.69
Permanent Ineff=
       F       F
Bank Sta=294.2,313.3
XS Rating Curve= 0 ,0
Exp/Cntr=0.3,0.1

Type RM Length L Ch R = 1 ,20925.7 ,56.7,47.8,38.5
XS GIS Cut Line= 5
      1821912.78      395149.855     1821927.103      395060.011
     1822140.645      394782.668     1822216.165      394741.001
      1822225.28      394632.928
#Sta/Elev= 30
       0 1067.45    27.3 1051.96      91  1014.7   100.7 1011.96   110.4 1011.26
   149.3 1012.28   188.2 1013.45   236.8 1015.71   246.6 1015.92   256.3 1015.67
   275.7 1014.12   285.4 1013.18   305.6 1010.24   314.6 1009.76   324.3 1010.11
     334 1010.75   343.8 1011.16   353.5 1011.28   402.1 1010.97   431.3 1011.16
     441  1012.5   450.6 1015.18   460.2 1018.59   469.8 1021.77   498.5 1029.31
   527.3 1036.46   545.3 1036.48   572.4 1036.97   599.6 1037.25   635.7 1036.86
#Mann= 3 , 0 , 0
       0     .08       0   305.6    .045       0   324.3      .1       0
#XS Ineff= 2 , 0
          244.91 1030.45
Permanent Ineff=
       F       F
Bank Sta=305.6,324.3
XS Rating Curve= 0 ,0
Exp/Cntr=0.3,0.1

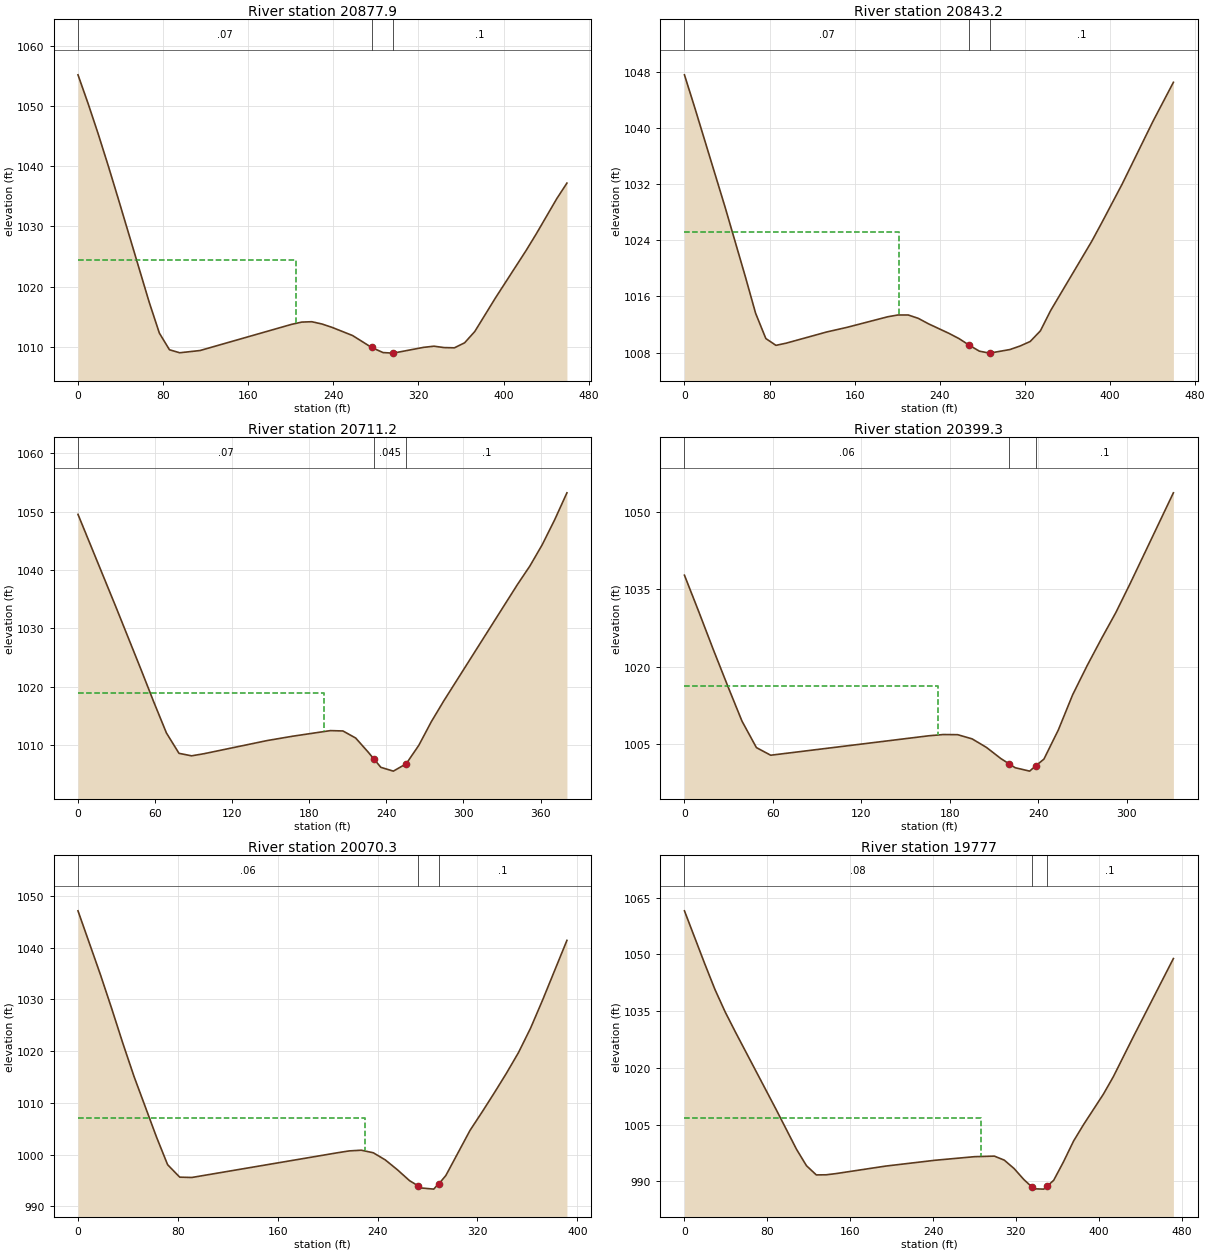
Type RM Length L Ch R = 1 ,20877.9 ,34.5,34.8,34.5
XS GIS Cut Line= 4
     1821966.165      395156.366     1822088.561      394962.355
     1822115.905      394860.793     1822217.467      394787.876
#Sta/Elev= 30
       0 1055.14     9.6 1050.33    19.1 1045.28    28.7  1039.9    38.2 1034.38
    66.9 1017.44    76.5 1012.29      86 1009.53    95.6 1009.03   114.7  1009.4
   200.7 1013.74   210.3 1014.12   219.8 1014.18   229.4  1013.8     239 1013.23
   258.1 1011.89     276 1009.91   286.8 1009.06   296.3 1008.97     325 1009.93
   334.6 1010.12   344.2 1009.89   353.8 1009.85   363.4 1010.68     373 1012.56
   392.3  1018.1   421.1 1025.96   430.8 1028.76     450 1034.58   459.6 1037.18
#Mann= 3 , 0 , 0
       0     .07       0     276    .045       0   296.3      .1       0
#XS Ineff= 2 , 0
          204.61 1024.41
Permanent Ineff=
       F       F
Bank Sta=276,296.3
XS Rating Curve= 0 ,0
Exp/Cntr=0.3,0.1

Type RM Length L Ch R = 1 ,20843.2 ,118.6,131.9,145.4
XS GIS Cut Line= 4
     1821997.415      395166.782     1822119.811      394972.772
     1822147.155      394871.209     1822248.717      394798.293
#Sta/Elev= 30
       0 1047.61     9.6 1042.97    38.2 1028.74    57.4 1018.74    66.9  1013.6
    76.5    1010      86 1009.03    95.6 1009.34   133.8 1010.94   152.9  1011.6
   191.2 1013.11   200.7 1013.36   210.3 1013.36   219.8 1012.88   229.4  1012.1
   248.5 1010.75   258.1 1009.99   267.6 1009.06   277.2  1008.2   286.8 1007.92
   305.9 1008.43   315.4 1008.93     325 1009.58   334.6  1011.1   344.2 1013.99
   382.7 1023.83   392.3 1026.52   411.5 1032.05   440.4 1040.98   459.6 1046.54
#Mann= 3 , 0 , 0
       0     .07       0   267.6    .045       0   286.8      .1       0
#XS Ineff= 2 , 0
          201.95 1025.26
Permanent Ineff=
       F       F
Bank Sta=267.6,286.8
XS Rating Curve= 0 ,0
Exp/Cntr=0.3,0.1

Type RM Length L Ch R = 1 ,20711.2 ,311.6,312,312.7
XS GIS Cut Line= 3
     1822016.947      395194.126     1822223.978      395013.136
     1822316.426      394962.355
#Sta/Elev= 26
       0 1049.53    29.5 1033.67    49.1 1022.92    58.9 1017.43    68.8 1012.09
    78.6 1008.59    88.4 1008.16    98.2 1008.53   147.3 1010.78     167 1011.52
   196.4 1012.48   206.2 1012.42   216.1 1011.21   225.9 1008.78   230.4 1007.59
   235.7 1006.19   245.4 1005.54   255.4 1006.79   265.2 1009.95     275 1014.02
   284.6 1017.55   342.1 1037.55   351.7 1040.69   361.3 1044.34   370.9 1048.57
   380.5 1053.22
#Mann= 3 , 0 , 0
       0     .07       0   230.4    .045       0   255.4      .1       0
#XS Ineff= 2 , 0
          191.32 1018.98
Permanent Ineff=
       F       F
Bank Sta=230.4,255.4
XS Rating Curve= 0 ,0
Exp/Cntr=0.3,0.1

Type RM Length L Ch R = 1 ,20399.3 ,330.1,329,327.7
XS GIS Cut Line= 2
     1822227.884      395418.084     1822480.488      395203.241
#Sta/Elev= 25
       0 1037.77     9.8 1030.64    19.5 1023.41    29.3 1016.34      39 1009.51
    48.8 1004.37    58.5 1002.89   165.8 1006.66   175.6  1006.9   185.3 1006.87
   195.1 1006.06   204.8 1004.41   214.6 1002.24   220.2 1001.22   224.3 1000.47
   234.1  999.81  238.09  1000.8   243.8 1002.14   253.6 1007.81   263.3 1014.62
   273.1 1020.25   282.8 1025.47   292.6 1030.55   302.4 1036.23   331.6 1053.73
#Mann= 3 , 0 , 0
       0     .06       0   220.2    .045       0  238.09      .1       0
#XS Ineff= 2 , 0
          171.74 1016.34
Permanent Ineff=
       F       F
Bank Sta=220.2,238.09
XS Rating Curve= 0 ,0
Exp/Cntr=0.3,0.1

Type RM Length L Ch R = 1 ,20070.3 ,298.2,293.4,288.4
XS GIS Cut Line= 4
      1822437.52      395687.616     1822489.603      395638.136
     1822665.384       395471.47     1822709.655      395407.668
#Sta/Elev= 30
       0  1047.1      18 1034.76    26.9  1028.3    35.9 1021.54    44.9  1015.1
    62.9  1003.4    71.8  998.06    81.5  995.65    91.2  995.59   207.5 1000.35
   217.2 1000.72   226.9 1000.86   236.6 1000.36   246.2  998.98   255.9  997.08
   265.6  994.98   272.2  994.01   275.3  993.56     285  993.34   287.2  993.94
  289.11  994.36   294.7  995.97   314.1  1004.7   323.8 1008.26   333.5 1011.93
   343.2 1015.71   352.9 1019.72   362.6 1024.45   372.3 1029.92   391.7 1041.39
#Mann= 3 , 0 , 0
       0     .06       0   272.2    .045       0  289.11      .1       0
#XS Ineff= 2 , 0
          229.58 1006.99
Permanent Ineff=
       F       F
Bank Sta=272.2,289.11
XS Rating Curve= 0 ,0
Exp/Cntr=0.3,0.1

Type RM Length L Ch R = 1 ,19777   ,332.5,328.8,324.8
XS GIS Cut Line= 4
     1822675.801      395942.824     1822744.811      395859.491
     1822889.342      395645.949     1822938.822      395552.199
#Sta/Elev= 30
       0 1061.54    19.7 1047.46    29.5 1040.71    39.3 1034.81    49.2 1029.49
    88.5 1009.01   108.2  998.48   117.8  994.14   127.3   991.7   136.8  991.73
   146.4  992.05   194.2  994.03   241.9  995.57   280.1  996.52   299.2  996.67
   308.8  995.61   318.3  993.38   327.8  990.45   335.1  988.61   337.4  988.03
     347  987.94   350.1   988.7   356.5  990.27     366  995.17   375.7 1000.65
   385.3 1004.98   404.6  1013.1   414.2 1017.72   433.5 1028.28   472.1 1048.92
#Mann= 3 , 0 , 0
       0     .08       0   335.1    .045       0   350.1      .1       0
#XS Ineff= 2 , 0
          286.09 1006.75
Permanent Ineff=
       F       F
Bank Sta=335.1,350.1
XS Rating Curve= 0 ,0
Exp/Cntr=0.3,0.1

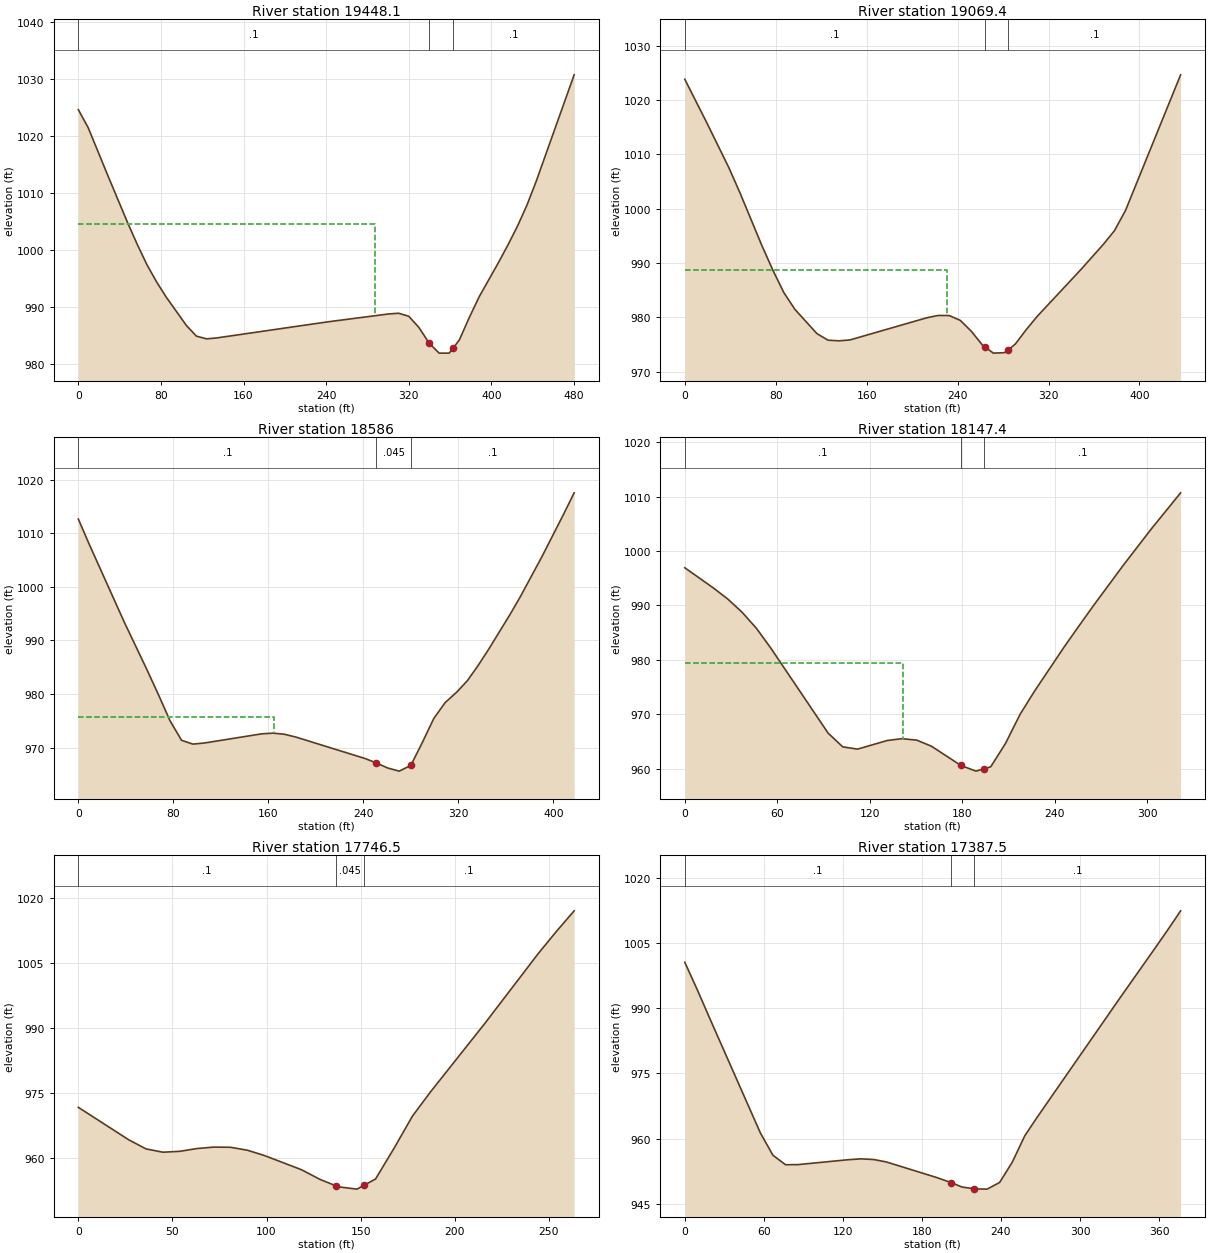
Type RM Length L Ch R = 1 ,19448.1 ,388.2,378.7,368.6
XS GIS Cut Line= 4
      1822981.79       396127.72     1823050.801      396062.616
     1823173.197      395795.688     1823208.353      395711.053
#Sta/Elev= 30
       0 1024.63     9.5 1021.48    28.5 1013.09    47.4 1004.91    56.9 1001.02
    66.4   997.4    75.9  994.33    85.4  991.62   104.7   986.7   114.4  984.83
   124.2  984.36     134  984.52   241.7  987.35   300.4  988.73   310.2  988.86
     320  988.33   329.8  986.37   339.6  983.65   349.4  981.85   359.2  981.85
   362.9  982.72     369  984.16   378.7  988.13   388.5  991.85   406.8  997.73
     416 1000.83   425.2 1004.12   434.4 1007.81   443.5 1012.07   480.2 1030.75
#Mann= 3 , 0 , 0
       0      .1       0   339.6    .045       0   362.9      .1       0
#XS Ineff= 2 , 0
          286.98 1004.57
Permanent Ineff=
       F       F
Bank Sta=339.6,362.9
XS Rating Curve= 0 ,0
Exp/Cntr=0.3,0.1

Type RM Length L Ch R = 1 ,19069.4 ,471.6,483.4,495.5
XS GIS Cut Line= 2
     1823520.853      396194.126     1823522.155      395757.928
#Sta/Elev= 30
       0  1023.8    19.4 1015.79    38.8 1007.53    48.5 1002.94    67.8  993.23
    77.6  988.64    87.2  984.55    96.9  981.48   116.3  977.02     126  975.82
   135.7   975.7   145.4  975.87   213.2  979.96     223  980.37   232.6  980.35
   242.3  979.47     252  977.48   261.7  974.96   263.8  974.63   271.4  973.44
   281.1  973.52  284.77  974.06   290.8  975.12   300.5  977.79   310.2  980.24
     349  988.93   368.4  993.49     378  995.96   387.7  999.67   436.2 1024.62
#Mann= 3 , 0 , 0
       0      .1       0   263.8    .045       0  284.77      .1       0
#XS Ineff= 2 , 0
          230.74  988.75
Permanent Ineff=
       F       F
Bank Sta=263.8,284.77
XS Rating Curve= 0 ,0
Exp/Cntr=0.3,0.1

Type RM Length L Ch R = 1 ,18586   ,438.8,438.6,437.8
XS GIS Cut Line= 3
     1823861.999      396168.084     1824020.853      395892.043
     1824084.655      395816.522
#Sta/Elev= 30
       0 1012.64     9.6 1007.73    38.6  993.45    57.9  984.47    67.6   979.8
    77.2  975.01    86.9  971.36    96.5  970.65   106.2  970.86   154.4  972.57
   164.1   972.7   173.7  972.48   183.4  971.95   241.3  967.97   250.9  967.14
   260.6  966.18   270.2  965.61   279.9  966.68   289.5  970.91   299.2  975.42
   308.8   978.4   318.5  980.34   327.5  982.48   336.5   985.3   345.4  988.34
   363.4  994.83   372.4  998.28   390.4 1005.68   408.4  1013.5   417.4 1017.54
#Mann= 3 , 0 , 0
       0      .1       0   250.9    .045       0   279.9      .1       0
#XS Ineff= 2 , 0
          164.94  975.75
Permanent Ineff=
       F       F
Bank Sta=250.9,279.9
XS Rating Curve= 0 ,0
Exp/Cntr=0.3,0.1

Type RM Length L Ch R = 1 ,18147.4 ,386.3,400.9,415.2
XS GIS Cut Line= 4
     1824286.478      396354.282     1824304.707      396263.136
     1824364.603      396153.761     1824436.217      396078.241
#Sta/Elev= 26
       0  996.94    18.6  993.21    27.9  991.18    37.2  988.75    46.5  985.79
    55.8  982.16      93  966.52   102.5  963.99   112.1  963.58   131.3  965.16
   140.9   965.5   150.5  965.23   160.1   964.1   179.1  960.58   188.9  959.53
   194.1  959.96   198.5  960.33   208.1  964.63   217.6  970.01   227.1  974.32
     246  982.31   255.5  986.14     265  989.91   283.9  997.17   302.8 1004.12
   321.7 1010.72
#Mann= 3 , 0 , 0
       0      .1       0   179.1    .045       0   194.1      .1       0
#XS Ineff= 2 , 0
          141.36  979.46
Permanent Ineff=
       F       F
Bank Sta=179.1,194.1
XS Rating Curve= 0 ,0
Exp/Cntr=0.3,0.1

Type RM Length L Ch R = 1 ,17746.5 ,371.6,359,346.1
XS GIS Cut Line= 4
     1824505.228      396468.866      1824600.28      396441.522
     1824670.592      396406.366     1824735.697      396350.376
#Sta/Elev= 24
       0  971.78      27  964.23      36  962.18      45  961.42      54  961.63
    62.9  962.26    71.9   962.6    80.9  962.56    89.9  961.87    98.9  960.65
   118.6  957.37   128.4  955.14   136.7  953.69   138.2  953.43     148   952.9
   151.7  953.77   157.9  955.24   167.7  962.32   177.5  969.76   187.1  975.35
   215.7  991.01   244.3 1007.26   253.8  1012.3   263.4 1017.14
#Mann= 3 , 0 , 0
       0      .1       0   136.7    .045       0   151.7      .1       0
Bank Sta=136.7,151.7
XS Rating Curve= 0 ,0
Exp/Cntr=0.3,0.1

Type RM Length L Ch R = 1 ,17387.5 ,354.4,356.4,357.9
XS GIS Cut Line= 3
     1824769.551      396863.397     1824902.363      396642.043
     1824953.145      396535.272
#Sta/Elev= 25
       0 1000.57     9.6  994.17    19.1  987.56    57.4  961.31    66.9  956.19
    76.5  954.01      86  954.04   124.3  955.17   133.8  955.36   143.4  955.21
     153  954.65   191.2  951.07   202.1  949.91   210.3   948.9   219.9  948.45
   229.5   948.4     239  949.93   248.6   954.6   258.1  960.67   267.2  964.79
   276.3  968.77   330.9   992.6   358.2 1004.34   367.3 1008.31   376.4  1012.4
#Mann= 3 , 0 , 0
       0      .1       0   202.1    .045       0   219.9      .1       0
Bank Sta=202.1,219.9
XS Rating Curve= 0 ,0
Exp/Cntr=0.3,0.1

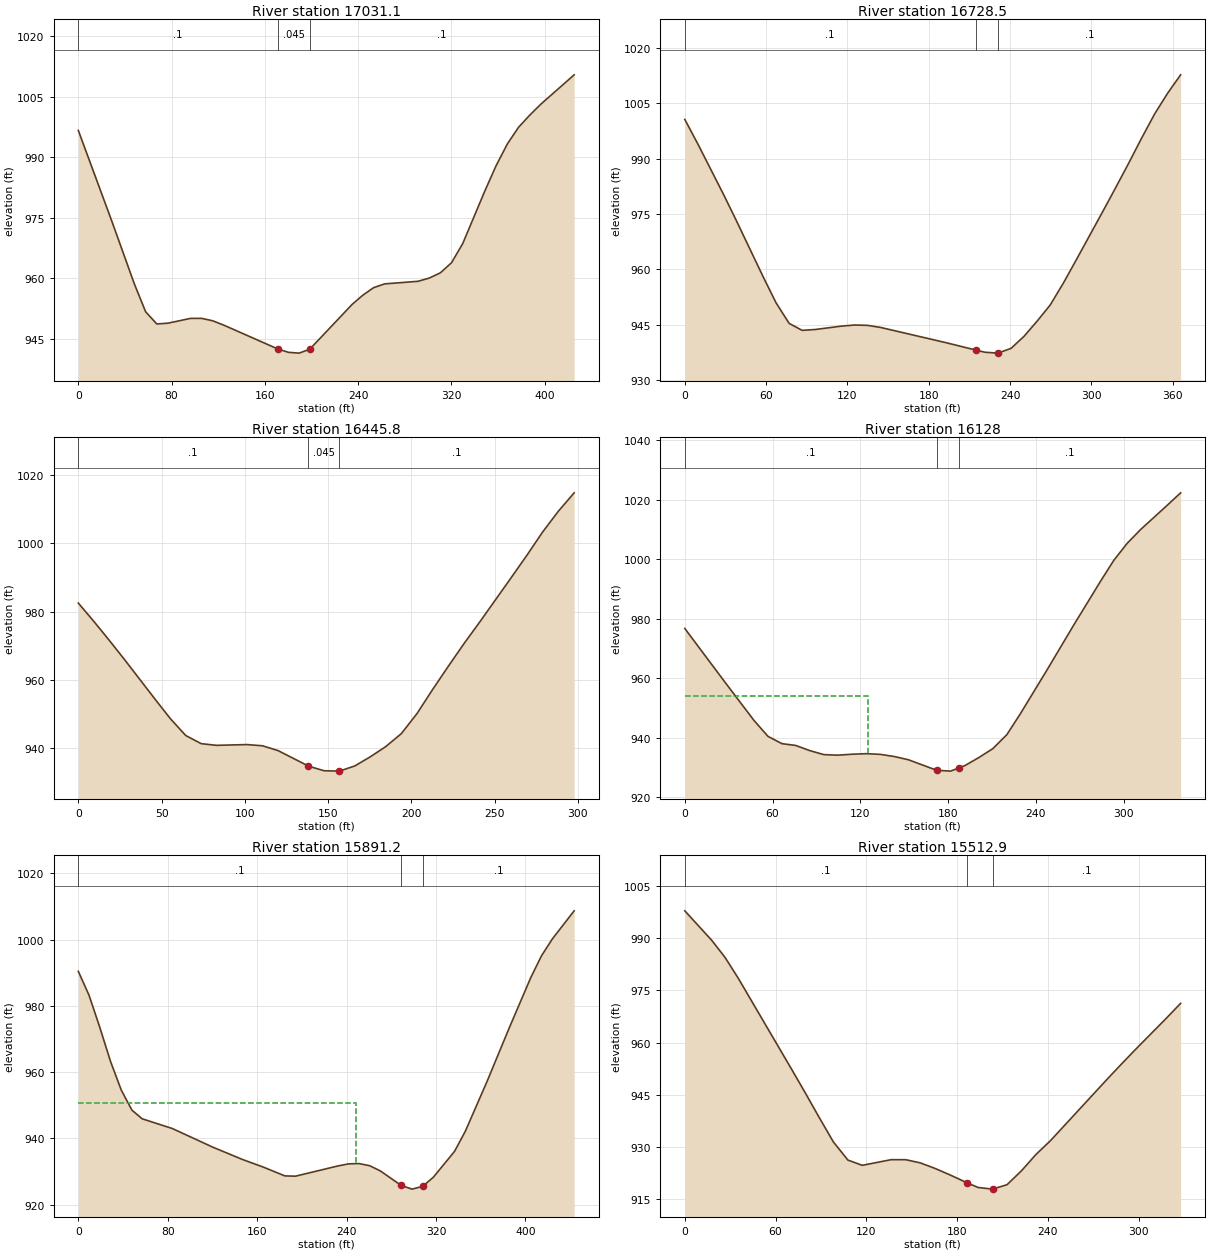
Type RM Length L Ch R = 1 ,17031.1 ,292.7,302.6,312.2
XS GIS Cut Line= 4
     1825082.051      396961.053     1825164.082      396854.282
     1825233.092      396757.928     1825223.978      396586.053
#Sta/Elev= 30
       0  996.65    28.8  974.13    48.1  958.61    57.7  951.76    67.3  948.72
    76.9  948.92    96.2   950.1   105.8  950.11   115.4   949.5     125   948.4
   171.1  942.53   180.2   941.7   189.4   941.5   198.5  942.47   234.9  953.58
     244  955.84   253.2   957.7   262.7  958.65   291.4  959.29     301  960.09
   310.5  961.38   320.1  963.89   329.7  968.62   348.8  981.73   358.3  987.89
   367.9  993.26   377.5   997.4     387 1000.38   396.6 1003.13   425.3 1010.43
#Mann= 3 , 0 , 0
       0      .1       0   171.1    .045       0   198.5      .1       0
Bank Sta=171.1,198.5
XS Rating Curve= 0 ,0
Exp/Cntr=0.3,0.1

Type RM Length L Ch R = 1 ,16728.5 ,276.1,282.7,288.7
XS GIS Cut Line= 2
     1825220.072      397112.095     1825536.478      396928.501
#Sta/Elev= 30
       0 1000.63     9.6     994    28.9  980.08    38.5  972.87    57.8  958.02
    67.4  950.92      77  945.39    86.6   943.5    96.3  943.74   115.5  944.65
   125.2  944.95   134.8  944.86   144.4   944.3   192.5  940.19   214.6  938.18
   221.4  937.58     231  937.34   240.7  938.63   250.3   941.9   259.9  945.99
   269.6  950.38   279.2  956.24   288.8  962.58     308  975.44   317.7  982.02
   327.3  988.64   336.9  995.47   346.6 1002.09   356.2 1007.71   365.8  1012.7
#Mann= 3 , 0 , 0
       0      .1       0   214.6    .045       0     231      .1       0
Bank Sta=214.6,231
XS Rating Curve= 0 ,0
Exp/Cntr=0.3,0.1

Type RM Length L Ch R = 1 ,16445.8 ,322.8,317.8,312.9
XS GIS Cut Line= 4
     1825324.238      397334.751     1825423.197      397285.272
     1825494.811      397267.043      1825606.79      397250.116
#Sta/Elev= 30
       0  982.49     9.2  977.19    18.4  971.68    27.7  965.96    46.1  954.31
    55.3   948.6    64.5  943.67    73.8  941.28      83  940.79   101.4  941.01
   110.6  940.66   119.9  939.26   137.7  934.85   138.4  934.67   147.6  933.34
   156.8  933.23   166.1  934.76   175.3  937.41   184.5  940.37     194  944.22
   203.4  950.09   212.8  957.16   222.3  964.02   231.7  970.65   241.2  977.01
     260  989.95   269.5  996.55   278.9 1003.34   288.4 1009.46   297.8  1014.8
#Mann= 3 , 0 , 0
       0      .1       0   137.7    .045       0   156.8      .1       0
Bank Sta=137.7,156.8
XS Rating Curve= 0 ,0
Exp/Cntr=0.3,0.1

Type RM Length L Ch R = 1 ,16128   ,248.6,236.9,225.2
XS GIS Cut Line= 4
     1825389.342      397644.647     1825462.259      397623.813
     1825591.165      397558.709     1825684.915      397485.793
#Sta/Elev= 30
       0  976.75    28.4  958.09    47.4   945.8    56.9  940.49    66.4  938.05
    75.8  937.45    85.5  935.71    95.1  934.36   104.7  934.18   114.3   934.5
     124  934.68   133.6  934.46   143.2  933.73   152.9  932.64   172.2  929.11
   181.7  928.82   187.2  929.86   191.4  930.65     201  933.37   210.6  936.37
   220.2  941.08   229.4  948.07   247.7  962.85   265.9  977.88   284.2  992.58
   293.3  999.63   302.5 1005.38   311.6 1009.97   329.9 1018.16     339 1022.32
#Mann= 3 , 0 , 0
       0      .1       0   172.2    .045       0   187.2      .1       0
#XS Ineff= 2 , 0
          124.93  954.13
Permanent Ineff=
       F       F
Bank Sta=172.2,187.2
XS Rating Curve= 0 ,0
Exp/Cntr=0.3,0.1

Type RM Length L Ch R = 1 ,15891.2 ,386.4,378.3,369.9
XS GIS Cut Line= 5
     1825526.061      397938.918     1825552.103      397898.553
     1825648.457      397849.074     1825748.717      397699.334
     1825782.572      397597.772
#Sta/Elev= 30
       0  990.43     9.6  983.21    19.2  973.54    28.8  963.26    38.4  954.61
      48  948.53    57.1  945.94    84.1     943   120.2  937.39   147.3   933.6
   165.8  931.32   184.8   928.7   194.3  928.62   232.2   931.7   241.7  932.33
   251.2  932.42   260.7  931.77   270.2  930.21   288.9  925.81   298.6  924.71
   308.1  925.55   317.6  928.29   336.6  936.11   346.3  942.22   365.8  957.31
   385.2  973.11   404.7  988.48   414.4  995.14   424.2 1000.27   443.6  1008.7
#Mann= 3 , 0 , 0
       0      .1       0   288.9    .045       0   308.1      .1       0
#XS Ineff= 2 , 0
          248.01  950.74
Permanent Ineff=
       F       F
Bank Sta=288.9,308.1
XS Rating Curve= 0 ,0
Exp/Cntr=0.3,0.1

Type RM Length L Ch R = 1 ,15512.9 ,550.8,550.5,550.1
XS GIS Cut Line= 3
     1826066.426      398004.022     1826070.332       397915.48
     1826123.717      397682.407
#Sta/Elev= 27
       0  997.88    17.7  989.46    26.6   984.5    35.4  978.46    70.9  952.12
    79.8  945.43    88.6  938.66    98.2  931.46   107.8  926.24   117.3  924.73
   136.4  926.36     146  926.35   155.6  925.44   165.1  923.89   174.7  922.09
   186.5  919.73   193.8  918.37   203.4  917.89     213  919.17   222.5  923.16
   232.1  927.85   241.7  931.83   279.9  949.84   289.5  954.25     299  958.53
   318.2  966.98   327.7  971.29
#Mann= 3 , 0 , 0
       0      .1       0   186.5    .045       0   203.4      .1       0
Bank Sta=186.5,203.4
XS Rating Curve= 0 ,0
Exp/Cntr=0.3,0.1

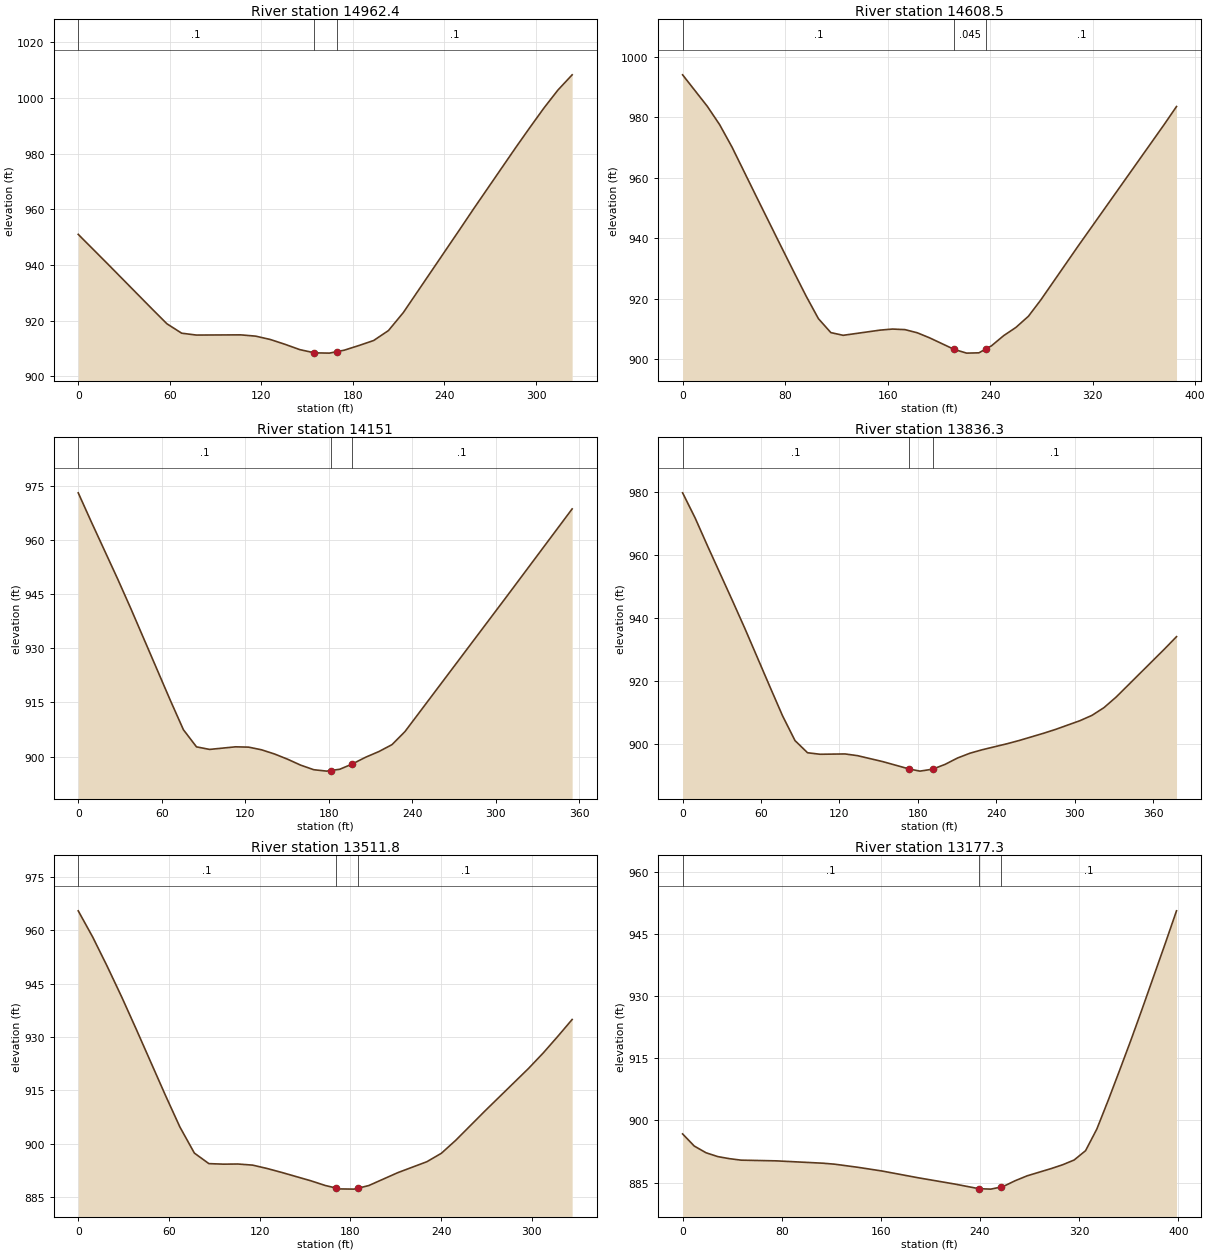
Type RM Length L Ch R = 1 ,14962.4 ,359.1,354,348.6
XS GIS Cut Line= 3
     1826597.676      398087.355     1826641.947      397879.022
     1826658.874      397769.647
#Sta/Elev= 27
       0  950.98    19.4  940.31    48.4  924.18    58.1  918.86    67.8  915.47
    77.4   914.8   106.5  914.87   116.2  914.42   125.8  913.22   135.5  911.48
   145.2  909.57   154.3  908.48   154.9  908.41   164.6  908.31   169.3  908.82
   174.3  909.36   183.9  911.03   193.6  912.84   203.3  916.41     213  922.84
   249.9  952.63   259.1  960.13   286.8  982.22     296  989.36   305.2  996.36
   314.4 1002.83   323.7 1008.29
#Mann= 3 , 0 , 0
       0      .1       0   154.3    .045       0   169.3      .1       0
Bank Sta=154.3,169.3
XS Rating Curve= 0 ,0
Exp/Cntr=0.3,0.1

Type RM Length L Ch R = 1 ,14608.5 ,456.3,457.5,458.6
XS GIS Cut Line= 2
     1826989.603      398174.595     1826980.488      397789.178
#Sta/Elev= 28
       0  994.12    19.3  983.68    28.9  977.62    38.6  970.16    57.8   953.6
    77.1  937.09    86.7  928.95    96.4  920.84     106  913.36   115.7  908.74
   125.3  907.84   154.2  909.56   163.8  909.91   173.5  909.73   183.1  908.69
   192.8     907     212  903.17   221.7  901.94   231.3  902.04   236.9  903.37
     241  904.34   250.6  907.73   260.2  910.47   269.9  914.15   279.5  919.51
   308.4  937.21   375.9  977.68   385.5  983.62
#Mann= 3 , 0 , 0
       0      .1       0     212    .045       0   236.9      .1       0
Bank Sta=212,236.9
XS Rating Curve= 0 ,0
Exp/Cntr=0.3,0.1

Type RM Length L Ch R = 1 ,14151   ,300.8,314.7,326.7
XS GIS Cut Line= 4
     1827420.592      398106.886      1827437.52      398023.553
     1827441.426      397873.813     1827432.311      397754.022
#Sta/Elev= 25
       0  973.02     9.4  964.98    28.4  949.12    37.8  940.98    66.1  915.65
    75.6  907.43      85  902.69    94.4  901.98   113.1   902.7   122.5  902.61
   131.8  901.87   141.2   900.7   150.6  899.25   159.9  897.62   169.3  896.36
   178.6  895.97   181.7  896.14     188  896.49   196.7   897.9   206.7  899.84
   216.1  901.39   225.5   903.3   234.8   906.9   308.8  944.75     355  968.57
#Mann= 3 , 0 , 0
       0      .1       0   181.7    .045       0   196.7      .1       0
Bank Sta=181.7,196.7
XS Rating Curve= 0 ,0
Exp/Cntr=0.3,0.1

Type RM Length L Ch R = 1 ,13836.3 ,322,324.5,327.9
XS GIS Cut Line= 3
     1827601.582      398183.709     1827744.811      397980.584
     1827755.228      397851.678
#Sta/Elev= 30
       0   979.7     9.6   971.7    19.1   962.8    38.2  945.36    47.8  936.44
    66.9  917.97    76.5   908.8      86  900.95    95.6  897.08   105.2   896.6
   124.3   896.7   133.8  896.16     153  894.28   173.6   891.9   181.6  891.24
   191.2  891.85   200.8  893.38   210.3   895.4   219.9  896.94   229.4  898.05
   248.5  899.97   257.8  901.01   276.3  903.29   285.5  904.52     304  907.27
   313.2  908.96   322.4  911.42   331.7  914.78   368.6  930.01   377.9  933.98
#Mann= 3 , 0 , 0
       0      .1       0   173.6    .045       0   191.2      .1       0
Bank Sta=173.6,191.2
XS Rating Curve= 0 ,0
Exp/Cntr=0.3,0.1

Type RM Length L Ch R = 1 ,13511.8 ,339.2,334.4,329.4
XS GIS Cut Line= 2
     1827846.374      398355.584      1828062.52      398110.793
#Sta/Elev= 30
       0  965.45     9.6  958.05    19.2  949.81    28.8  941.18    38.4  932.12
    57.6  913.63    67.2  904.69    76.8  897.33    86.4  894.37      96  894.22
   105.6  894.26   115.3  893.95   124.9     893   134.5   891.9   153.7  889.56
   163.3  888.23   170.3  887.52   172.9  887.26   182.5   887.2   185.3  887.49
   192.1   888.2   211.3  891.83   230.5   894.9   240.1  897.27   249.7  900.96
   268.9  909.16   297.8  921.15   307.4  925.45     317   930.1   326.6   934.9
#Mann= 3 , 0 , 0
       0      .1       0   170.3    .045       0   185.3      .1       0
Bank Sta=170.3,185.3
XS Rating Curve= 0 ,0
Exp/Cntr=0.3,0.1

Type RM Length L Ch R = 1 ,13177.3 ,396.7,392.7,388.5
XS GIS Cut Line= 4
      1828100.28      398530.063     1828227.884      398432.407
      1828294.29      398312.616     1828328.145      398217.563
#Sta/Elev= 30
       0  896.75     9.4  893.82    18.9   892.2    28.4  891.27    37.8  890.77
    47.3  890.41    75.6  890.24   113.4  889.67   122.9  889.43   141.8  888.67
   160.7   887.8     190  886.16   219.4  884.65     239  883.52   248.7  883.41
   256.6  883.89   258.5  884.01   268.3  885.43   278.1  886.63   297.6  888.39
   306.8  889.31     316  890.45   325.2   892.7   334.3  897.93   343.5  904.89
   352.7  912.13   361.9   919.5     371  927.06   389.4  942.68   398.6  950.66
#Mann= 3 , 0 , 0
       0      .1       0     239    .045       0   256.6      .1       0
Bank Sta=239,256.6
XS Rating Curve= 0 ,0
Exp/Cntr=0.3,0.1

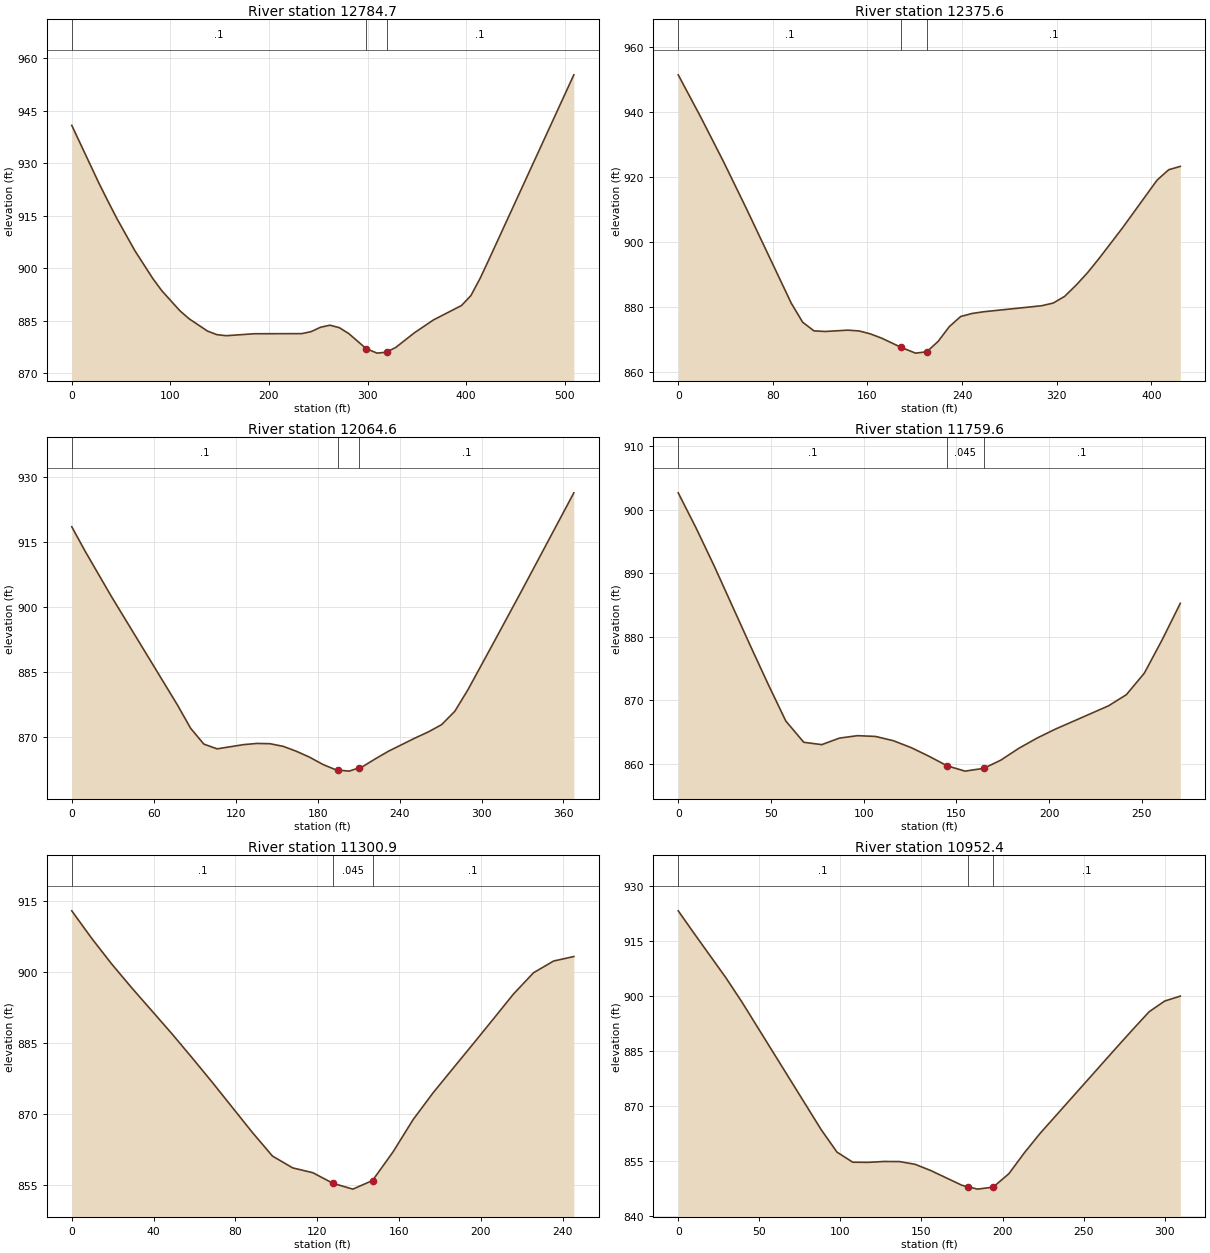
Type RM Length L Ch R = 1 ,12784.7 ,407.2,409.1,411.1
XS GIS Cut Line= 4
      1828606.79      398729.282     1828596.374      398601.678
      1828669.29       398384.23     1828653.665      398233.188
#Sta/Elev= 30
       0  940.86    27.4  924.43    36.6  919.25    45.7  914.27      64  905.05
    82.3  897.05    91.4  893.58   109.7  887.88   118.9  885.62   137.6  882.09
   147.1  881.06   156.7  880.76   185.4  881.32   233.2  881.35   242.7  881.92
   252.3  883.17   261.8  883.76   271.4  883.05   280.9  881.37   298.5  877.09
   309.6  875.78   319.2  876.05   328.7  877.43   347.8  881.65   366.9  885.28
   395.3  889.39   404.8  892.23   414.3  897.23   423.8  902.96   509.2   955.3
#Mann= 3 , 0 , 0
       0      .1       0   298.5    .045       0   319.2      .1       0
Bank Sta=298.5,319.2
XS Rating Curve= 0 ,0
Exp/Cntr=0.3,0.1

Type RM Length L Ch R = 1 ,12375.6 ,303.1,311,318.5
XS GIS Cut Line= 4
     1828984.395      398738.397      1829006.53      398635.532
     1829059.915      398513.136     1829179.707      398371.209
#Sta/Elev= 30
       0  951.54    19.1  938.49    38.3  924.81    57.4  910.56    95.6  881.25
   105.2  875.42   114.8  872.75   124.3  872.57   143.4  872.98   152.9  872.74
   162.4  871.84     172  870.51   188.6  867.66   200.6  865.91   210.1  866.32
   219.7   869.5   229.2  874.07   238.8  877.18   248.5  878.12   258.3  878.64
   307.2  880.49     317  881.31   326.7  883.37   336.5  886.86   346.3  890.76
     356  895.12   375.6  904.44   404.9  919.16   414.7  922.34   424.5  923.37
#Mann= 3 , 0 , 0
       0      .1       0   188.6    .045       0   210.1      .1       0
Bank Sta=188.6,210.1
XS Rating Curve= 0 ,0
Exp/Cntr=0.3,0.1

Type RM Length L Ch R = 1 ,12064.6 ,303.8,305,306.3
XS GIS Cut Line= 2
     1829171.895      398855.584     1829423.197      398587.355
#Sta/Elev= 29
       0  918.46     9.7  912.87      29  902.38    77.4  877.32      87  871.97
    96.7  868.31   106.4  867.21   125.7  868.18   135.4  868.46   145.1   868.4
   154.8  867.79   164.4  866.66   174.1  865.29   183.8  863.62   193.4  862.37
   195.2  862.31   203.1  862.07   210.2  862.81   212.8  863.08   222.5  864.95
   232.1   866.7   251.5  869.73   261.2  871.14   270.8   872.8   280.5   875.9
   290.2  880.93   309.5  892.09   328.9   903.4   367.6  926.29
#Mann= 3 , 0 , 0
       0      .1       0   195.2    .045       0   210.2      .1       0
Bank Sta=195.2,210.2
XS Rating Curve= 0 ,0
Exp/Cntr=0.3,0.1

Type RM Length L Ch R = 1 ,11759.6 ,460.4,458.7,456.7
XS GIS Cut Line= 2
     1829404.967      399037.876      1829600.28      398850.376
#Sta/Elev= 26
       0  902.68     9.7   897.1    19.3  891.23    38.7  878.74    48.4  872.62
      58  866.78    67.7  863.42    77.4  863.05      87  864.08    96.7  864.46
   106.4  864.34     116  863.67   125.7  862.57   135.4   861.2     145  859.72
   154.7  858.88   164.8  859.32     174  860.61   183.7  862.47   193.4  864.06
   203.1  865.45   232.1  869.16   241.7  870.91   251.4   874.3   261.1   879.6
   270.8  885.29
#Mann= 3 , 0 , 0
       0      .1       0     145    .045       0   164.8      .1       0
Bank Sta=145,164.8
XS Rating Curve= 0 ,0
Exp/Cntr=0.3,0.1

Type RM Length L Ch R = 1 ,11300.9 ,347.1,348.5,349.8
XS GIS Cut Line= 2
     1829727.884      399369.907     1829890.645      399186.313
#Sta/Elev= 27
       0   912.9     9.8  907.06    19.6  901.63    29.4   896.6    39.3  891.72
    49.1  886.88    58.9  881.83    68.7  876.69    78.5  871.39    88.3   866.1
    98.1  861.13     108  858.63   117.8  857.62   127.6  855.39     132  854.83
   137.4  854.15     147  855.97     157  861.99   166.8   868.8   176.6  874.48
   186.5  879.72   196.3  884.88   206.1  890.09   215.9  895.34   225.7  899.83
   235.5   902.3   245.4  903.25
#Mann= 3 , 0 , 0
       0      .1       0   127.6    .045       0     147      .1       0
Bank Sta=127.6,147
XS Rating Curve= 0 ,0
Exp/Cntr=0.3,0.1

Type RM Length L Ch R = 1 ,10952.4 ,424.3,422.8,421.2
XS GIS Cut Line= 4
     1829958.353      399589.959      1830037.78      399532.668
     1830126.322      399444.126     1830178.405      399375.116
#Sta/Elev= 24
       0  923.19     9.8  917.03    29.4  904.94    39.2  898.38    88.1  863.56
    97.9   857.4   107.6  854.65   117.2  854.61   126.8  854.85   136.5  854.82
   146.1  854.07   155.7  852.38     175  848.35   178.5  847.97   184.6  847.31
   194.2  847.86   203.9  851.52   213.5  857.25   223.2  862.54   271.2  886.38
   280.8  891.08   290.4  895.68     300   898.6   309.6  899.94
#Mann= 3 , 0 , 0
       0      .1       0   178.5    .045       0   194.2      .1       0
Bank Sta=178.5,194.2
XS Rating Curve= 0 ,0
Exp/Cntr=0.3,0.1