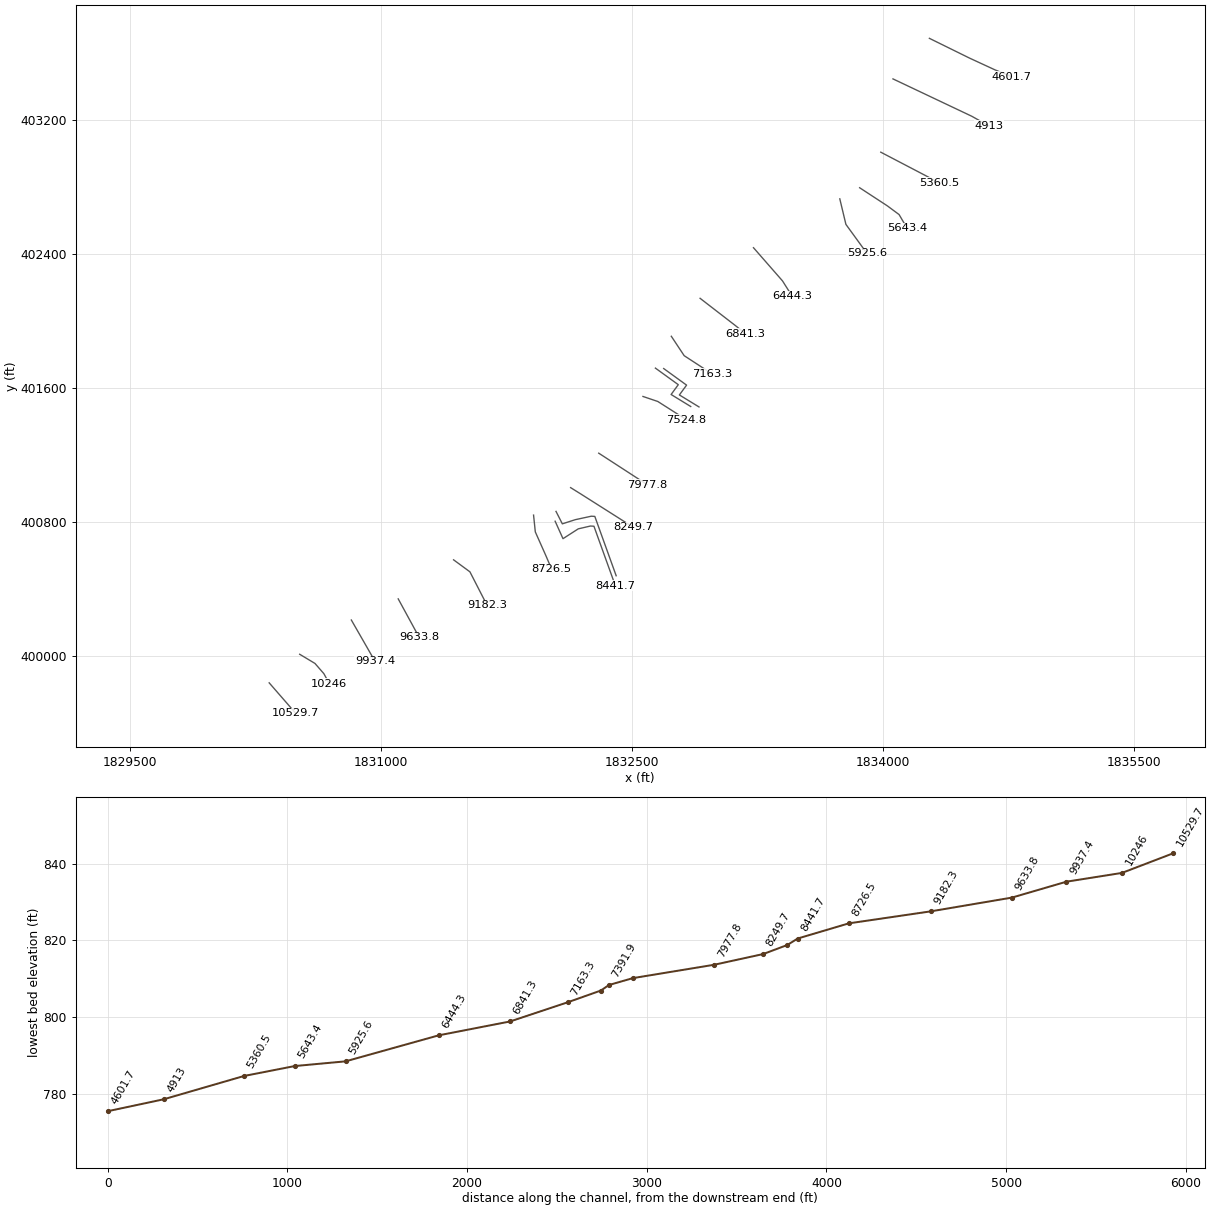
HEC-RAS study COALFORK.prj: COALFORK

--- COALFORK.g01 (geometry) --- (continued)

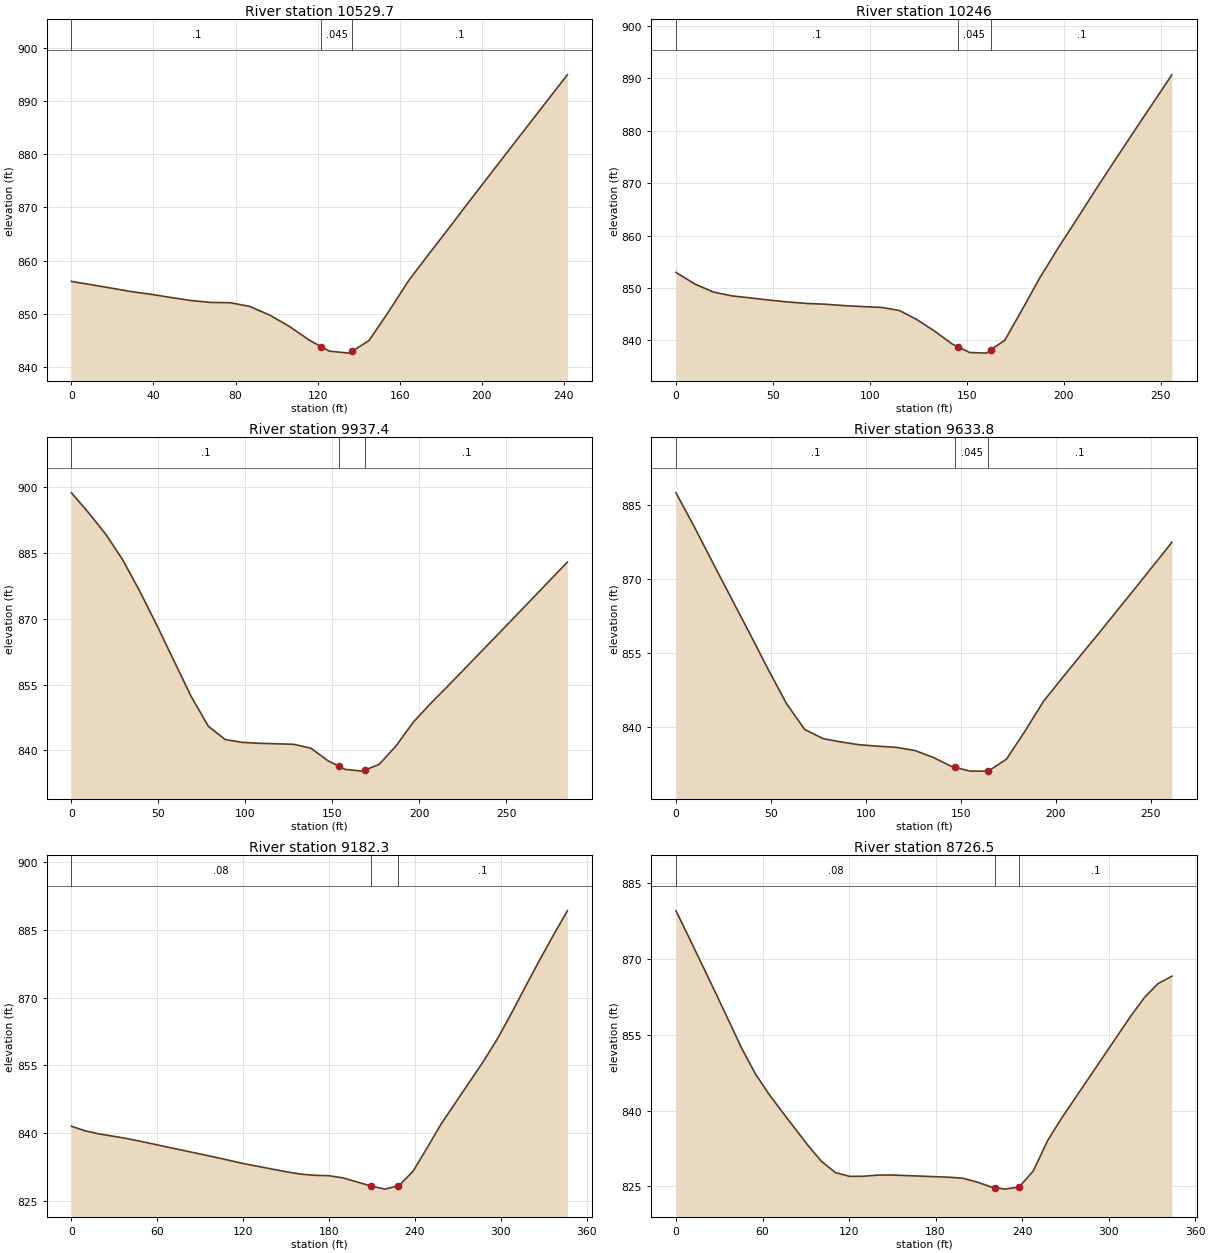
Type RM Length L Ch R = 1 ,10529.7 ,283.4,283.6,283.5
XS GIS Cut Line= 2
     1830332.051      399842.563     1830490.905      399660.272
#Sta/Elev= 28
       0   856.1     9.7  855.48    19.3  854.85      29   854.2    38.7  853.69
    48.4  853.09      58  852.53    67.7  852.16    77.4   852.1      87   851.4
    96.7  849.77   106.4  847.62   116.1  845.05   121.9  843.82   125.7  843.01
   135.4  842.64   136.9     843   145.1     845   154.8   850.5   164.4  856.24
   174.1  861.16   183.8  865.98   193.4  870.83   203.1  875.68   212.8  880.51
   222.4  885.28   232.1  890.09   241.8  894.88
#Mann= 3 , 0 , 0
       0      .1       0   121.9    .045       0   136.9      .1       0
Bank Sta=121.9,136.9
XS Rating Curve= 0 ,0
Exp/Cntr=0.3,0.1

Type RM Length L Ch R = 1 ,10246   ,313.3,308.7,304.4
XS GIS Cut Line= 4
     1830514.342      400013.136     1830605.488      399958.449
     1830658.874      399897.251     1830691.426      399837.355
#Sta/Elev= 30
       0  852.97     9.7  850.76    19.3  849.22      29  848.48    38.6  848.09
    48.3  847.68      58  847.32    67.6  847.04    77.3  846.89      87  846.62
    96.6  846.44   106.3  846.28   115.3  845.69   124.3  843.95   133.4  841.75
   142.4   839.3   145.2   838.8   151.4  837.68   160.2  837.56  162.36  838.21
   169.5  839.99   178.5  845.87   187.5  851.88   197.2  857.72     207  863.31
   216.7  868.94   226.5  874.47   236.2   879.9   245.9  885.27   255.7  890.69
#Mann= 3 , 0 , 0
       0      .1       0   145.2    .045       0  162.36      .1       0
Bank Sta=145.2,162.36
XS Rating Curve= 0 ,0
Exp/Cntr=0.3,0.1

Type RM Length L Ch R = 1 ,9937.4  ,304,303.6,303.1
XS GIS Cut Line= 2
     1830822.936      400217.563     1830964.863      399970.168
#Sta/Elev= 25
       0  898.68     9.8  894.16    19.7  889.26    29.5  883.41    39.3  876.24
    49.2  868.44    68.8  852.32    78.7  845.51    88.5  842.46    98.4  841.82
   108.2  841.62   127.9  841.39   137.7   840.5   147.5  837.65   153.9  836.38
   157.4  835.68   167.2  835.28   168.9  835.55     177  836.82   186.9  841.14
   196.7  846.49   206.5  850.67   216.4  854.63   245.9  866.69   285.2   882.9
#Mann= 3 , 0 , 0
       0      .1       0   153.9    .045       0   168.9      .1       0
Bank Sta=153.9,168.9
XS Rating Curve= 0 ,0
Exp/Cntr=0.3,0.1

Type RM Length L Ch R = 1 ,9633.8  ,452.1,451.5,451
XS GIS Cut Line= 2
     1831102.884      400343.866     1831227.884      400114.699
#Sta/Elev= 30
       0  887.45     9.7  880.53    19.3  873.37      29  866.21    38.7  859.08
    48.3   851.9      58   844.9    67.7  839.59    77.4  837.72      87  837.03
    96.7  836.47   106.4  836.18     116  835.95   125.7  835.31   135.4  833.92
     145   832.1   146.8  831.92   154.7  831.15   161.8  831.14   164.4  831.14
     174  833.59   183.7  839.24   193.4  845.25     203  849.84   212.7  854.44
   222.4  858.95     232  863.55   241.7  868.15   251.4  872.81     261  877.44
#Mann= 3 , 0 , 0
       0      .1       0   146.8    .045       0   164.4      .1       0
Bank Sta=146.8,164.4
XS Rating Curve= 0 ,0
Exp/Cntr=0.3,0.1

Type RM Length L Ch R = 1 ,9182.3  ,457.4,455.8,454.1
XS GIS Cut Line= 3
     1831433.613      400576.938      1831531.27      400505.324
     1831634.134      400304.803
#Sta/Elev= 26
       0  841.48     9.3   840.5    18.6  839.83    37.3  838.84    46.6  838.26
   102.5  834.49   121.1  833.16   150.5  831.38   160.3  830.88   170.1  830.62
   179.9  830.53   189.7  830.05   209.3  828.25   219.1  827.56   228.3   828.3
   228.9  828.35   238.7  831.53   248.5   836.7   258.3  841.99   287.7  855.78
   297.5  860.78   307.3  866.43   317.1  872.36   326.9  878.16   336.7  883.79
   346.5   889.2
#Mann= 3 , 0 , 0
       0     .08       0   209.3    .045       0   228.3      .1       0
Bank Sta=209.3,228.3
XS Rating Curve= 0 ,0
Exp/Cntr=0.3,0.1

Type RM Length L Ch R = 1 ,8726.5  ,252.8,284.8,316.5
XS GIS Cut Line= 4
     1831911.478      400843.866     1831921.895      400743.605
     1831985.697      400600.376     1832019.551      400520.949
#Sta/Elev= 28
       0  879.53     9.2  874.15    27.5  863.28    45.8  852.19      55   847.3
    64.2  843.35    73.3  839.87    91.6  833.07   100.8  829.97   110.6  827.71
   120.4  826.97   130.2  826.99     140  827.22   149.8  827.23     189   826.8
   198.8   826.6   208.6  825.86   218.4  824.89   221.3  824.76   228.2  824.44
     238  824.85   247.8  828.06   257.6  833.98   267.2  838.39   315.2  858.62
   324.8  862.34   334.3  865.12   343.9  866.59
#Mann= 3 , 0 , 0
       0     .08       0   221.3    .045       0     238      .1       0
Bank Sta=221.3,238
XS Rating Curve= 0 ,0
Exp/Cntr=0.3,0.1

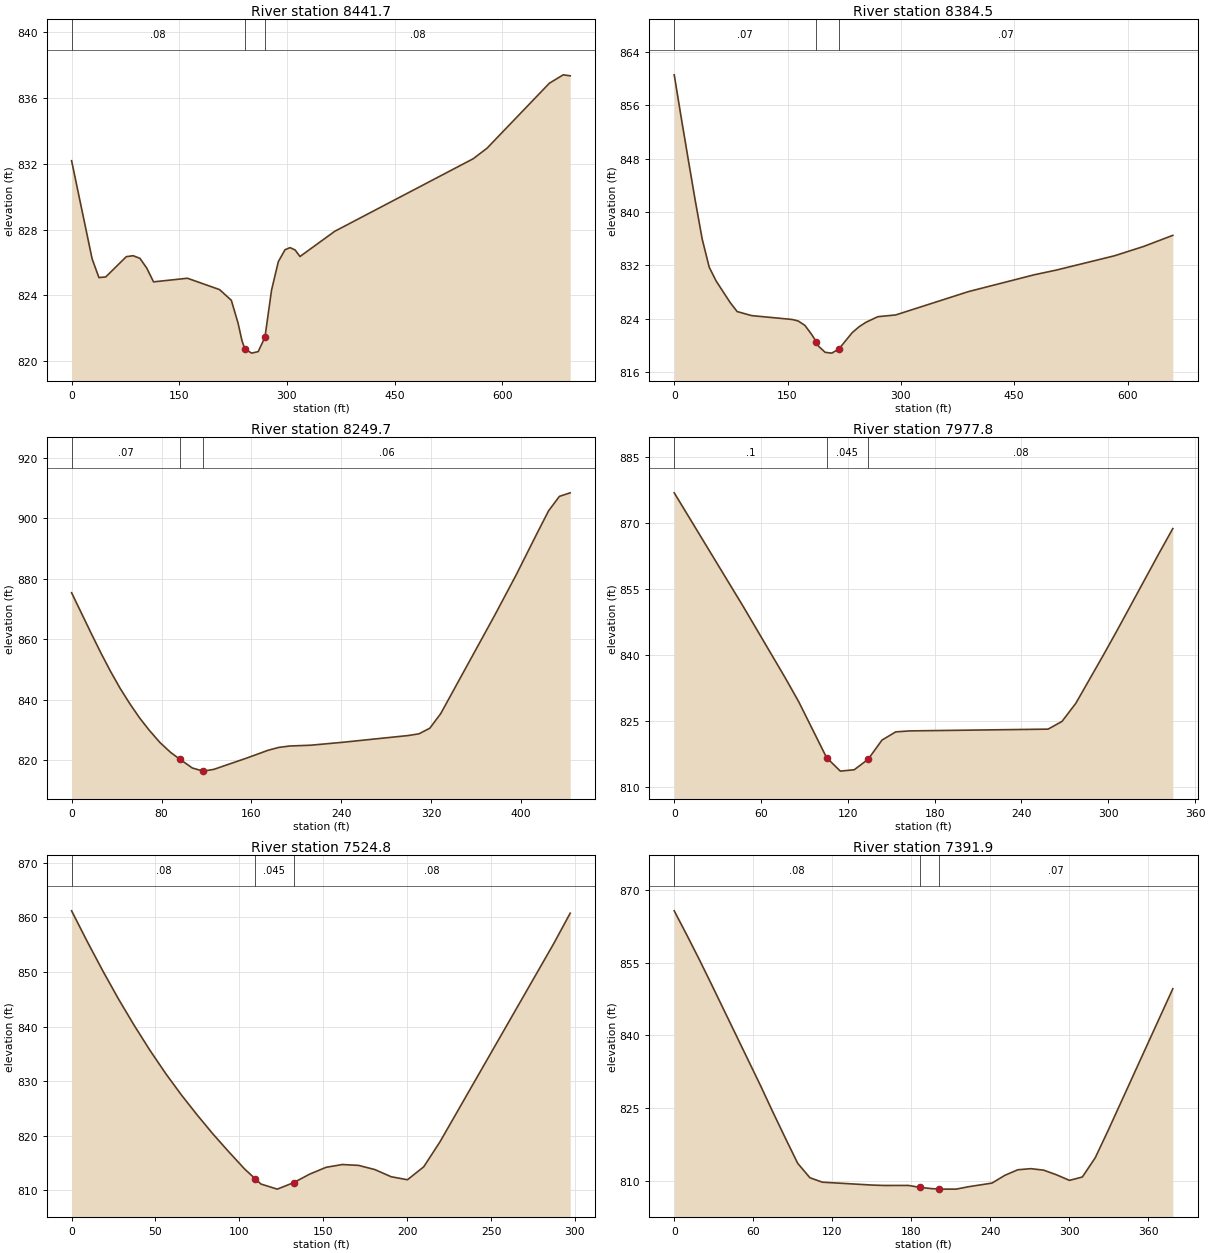
Type RM Length L Ch R = 1 ,8441.7  ,57.6,57.1,56.7
XS GIS Cut Line= 6
     1832040.384      400807.407     1832087.259      400703.241
     1832178.405      400761.834     1832251.322      400778.761
     1832272.155      400777.459     1832399.759      400423.293
#Sta/Elev= 30
       0  832.18    28.6  826.22    38.1  825.08    47.6  825.12    76.2  826.35
    85.7  826.41    95.2  826.25   104.7  825.66   114.2  824.82   161.4  825.04
   206.2  824.35   222.6   823.7     232  822.31  237.47  821.24   241.3  820.76
   250.7  820.49     260  820.58   269.4  821.45   278.7  824.33   288.1  826.05
   297.4  826.77   304.4   826.9   311.4  826.76   318.3  826.36   366.6  827.89
   559.6   832.3   578.9  832.94   665.8  836.89   685.1   837.4   694.8  837.34
#Mann= 3 , 0 , 0
       0     .08       0   241.3    .045       0   269.4     .08       0
Bank Sta=241.3,269.4
XS Rating Curve= 0 ,0
Exp/Cntr=0.3,0.1

Type RM Length L Ch R = 1 ,8384.5  ,152.4,134.9,116.9
XS GIS Cut Line= 6
     1832045.592      400866.001     1832083.353      400791.782
     1832160.176      400816.522      1832256.53      400837.355
     1832277.363      400836.053     1832404.967      400481.886
#Sta/Elev= 30
       0  860.59     9.2   854.2    18.5  847.92    27.8  841.73      37  835.95
    46.3  831.72    55.5  829.64      74  826.42    83.3  825.06   102.5  824.45
   156.3  823.87     164  823.65     173  822.98   181.9  821.62  187.87  820.56
   190.9  819.87   199.8  818.94   208.5  818.82   217.8  819.43   235.7  821.91
   244.6  822.77   253.6  823.44   269.5  824.29   293.1  824.55   389.6  828.06
   476.5  830.58   505.5  831.28   582.7  833.43   621.3  834.83   659.9   836.5
#Mann= 3 , 0 , 0
       0     .07       0  187.87    .045       0   217.8     .07       0
Bank Sta=187.87,217.8
XS Rating Curve= 0 ,0
Exp/Cntr=0.3,0.1

Type RM Length L Ch R = 1 ,8249.7  ,272.2,271.9,271.4
XS GIS Cut Line= 3
     1832132.832      401007.928     1832191.426       400971.47
     1832507.832      400770.949
#Sta/Elev= 30
       0  875.44    17.2   862.2    25.9  855.66    34.5  849.54    43.1  843.88
    51.8  838.75    60.4   834.1      69  830.02    78.6  825.92    88.2  822.61
    96.1  820.45   107.4  817.49     117  816.45   126.6  817.04   155.5  820.73
   174.7  823.33   184.3  824.29   193.9  824.75   213.1  825.03   241.9  826.01
   299.5  828.22   309.1  828.79   318.7  830.64   328.4  835.46   376.4  867.95
   395.6  881.38   414.8  895.59   424.4  902.54     434  907.31   443.6  908.48
#Mann= 3 , 0 , 0
       0     .07       0    96.1    .045       0     117     .06       0
Bank Sta=96.1,117
XS Rating Curve= 0 ,0
Exp/Cntr=0.3,0.1

Type RM Length L Ch R = 1 ,7977.8  ,452.7,453,453.2
XS GIS Cut Line= 2
     1832300.801      401213.657     1832589.863      401026.157
#Sta/Elev= 18
       0  876.77    47.8  850.94    76.6  834.89    86.1  829.37   105.3  816.74
   114.8  813.67   124.4  813.98     134  816.35   143.6  820.71   153.1  822.57
   162.7  822.79   258.4  823.19     268  824.94   277.6  829.07   296.7  840.04
   306.3   845.7     335  863.02   344.6  868.67
#Mann= 3 , 0 , 0
       0      .1       0   105.3    .045       0     134     .08       0
Bank Sta=105.3,134
XS Rating Curve= 0 ,0
Exp/Cntr=0.3,0.1

Type RM Length L Ch R = 1 ,7524.8  ,171.1,132.9,79
XS GIS Cut Line= 3
     1832565.124      401552.199     1832653.665      401522.251
      1832825.54      401412.876
#Sta/Elev= 27
       0  861.21     9.4  855.54    18.7  850.15      28  845.02    37.4  840.17
    46.7  835.64    56.1  831.38    65.4  827.48    74.8  823.81    84.1  820.36
    93.5   817.1   103.2  813.86   109.5  812.08   112.9  811.12   122.6  810.19
   132.3  811.37     142  812.95   151.7  814.19   161.4   814.7   171.1  814.54
   180.8  813.77   190.5  812.46   200.2  811.91   209.9  814.28   219.6  818.87
   287.5  855.26   297.2  860.78
#Mann= 3 , 0 , 0
       0     .08       0   109.5    .045       0   132.3     .08       0
Bank Sta=109.5,132.3
XS Rating Curve= 0 ,0
Exp/Cntr=0.3,0.1

Type RM Length L Ch R = 1 ,7391.9  ,49.6,45.7,58.9
XS GIS Cut Line= 4
     1832639.342       401721.47     1832776.061      401622.511
     1832733.092      401563.918      1832850.28      401492.303
#Sta/Elev= 30
       0  865.63     9.4  860.75    18.8  855.75    28.1  850.63    65.6  829.67
      75  824.22    84.4  818.91    93.8  813.71   103.1  810.74   112.5  809.83
     150  809.24   159.4  809.15   177.9  809.16   186.5  808.77     196  808.49
   201.5  808.44   205.1   808.4   214.2   808.4   223.3  808.88   241.4  809.64
   251.2  811.24     261  812.38   270.9  812.61   280.7   812.3   290.5  811.34
   300.3   810.2   310.1   810.9   319.9  814.87   329.7  820.49   378.8  849.61
#Mann= 3 , 0 , 0
       0     .08       0   186.5    .045       0   201.5     .07       0
Bank Sta=186.5,201.5
XS Rating Curve= 0 ,0
Exp/Cntr=0.3,0.1

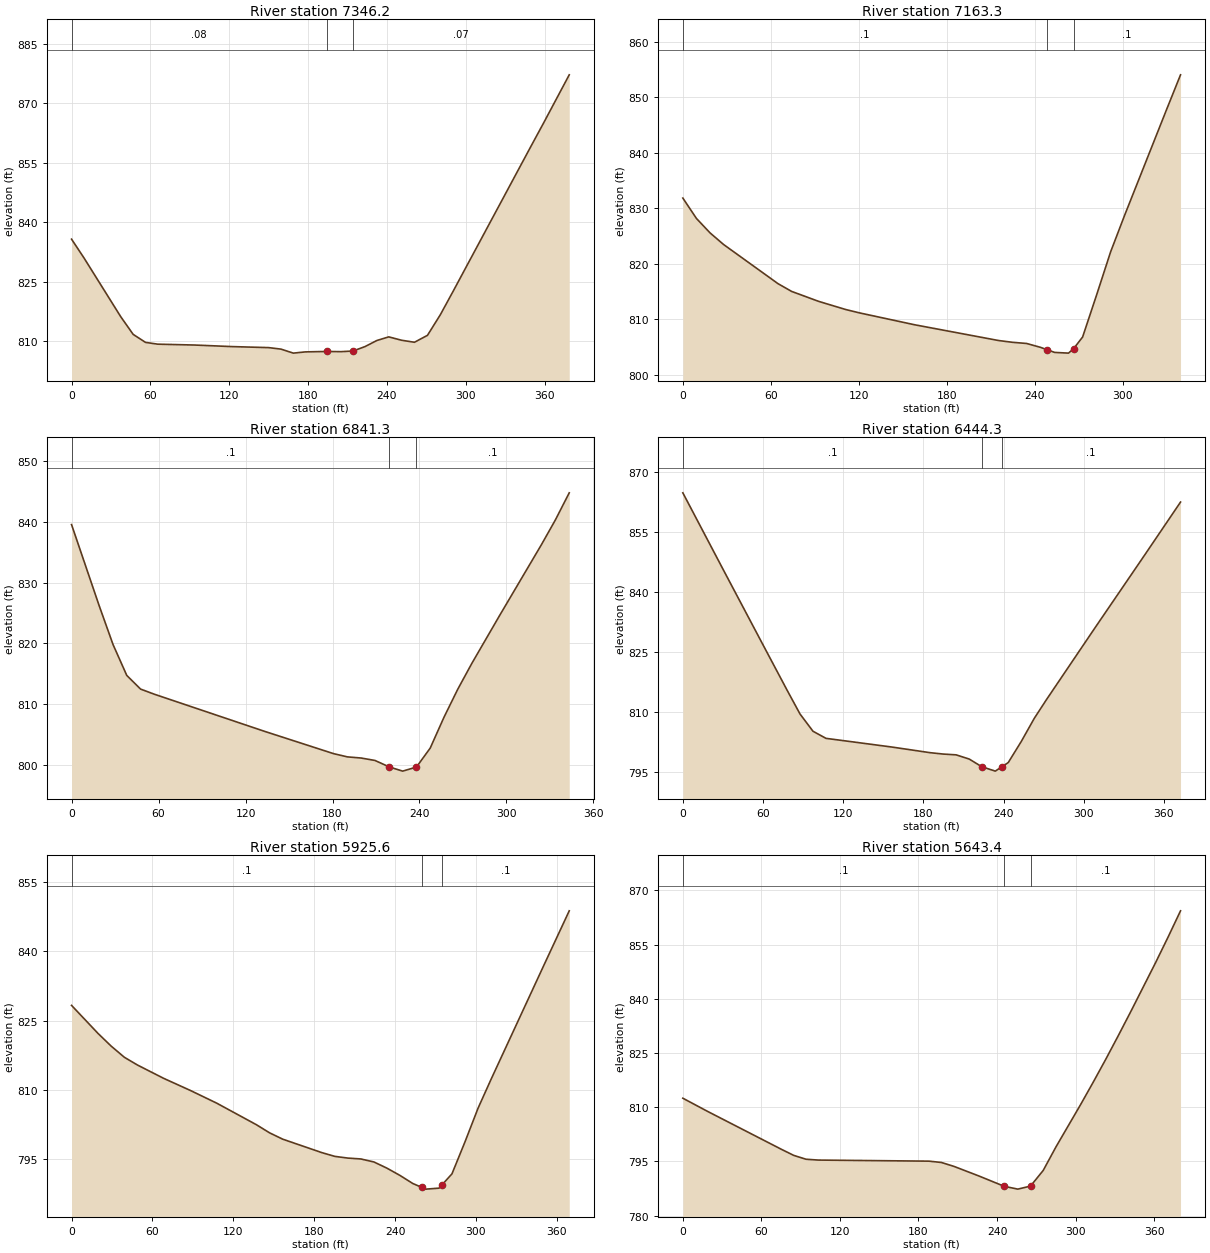
Type RM Length L Ch R = 1 ,7346.2  ,141.5,182.9,221
XS GIS Cut Line= 4
     1832688.822      401718.866      1832825.54      401619.907
     1832782.572      401561.313     1832899.759      401489.699
#Sta/Elev= 26
       0   835.7     9.4     831    37.5  816.11    46.9  811.68    56.3  809.66
    65.6  809.21    93.8  808.99   121.9   808.6     150  808.34   159.4  807.96
   168.8  806.95   177.9  807.26   194.3  807.37   205.1  807.32   214.2  807.48
   223.3  808.59   232.4  810.14   241.4  811.05   251.2   810.2     261  809.69
   270.9  811.44   280.7  816.64   290.5   822.6   349.3  858.91   359.2  864.96
   378.8  877.16
#Mann= 3 , 0 , 0
       0     .08       0   194.3    .045       0   214.2     .07       0
Bank Sta=194.3,214.2
XS Rating Curve= 0 ,0
Exp/Cntr=0.3,0.1

Type RM Length L Ch R = 1 ,7163.3  ,323.7,321.9,320.1
XS GIS Cut Line= 3
     1832734.395      401911.574     1832811.217      401795.688
     1832979.186      401686.313
#Sta/Elev= 24
       0  831.86     9.3  828.18    18.5   825.6    27.8  823.49    64.9  816.44
    74.2  815.04    92.7  813.24   111.2  811.77   120.5  811.17   158.1  809.03
   215.4  806.19   224.9  805.87   234.5  805.66     244  804.96   248.4  804.54
   253.6  804.05   263.1  803.92  266.61  804.74   272.7  806.82   282.2  814.36
   291.8  822.16   301.3  828.71   329.9  847.75   339.5  854.06
#Mann= 3 , 0 , 0
       0      .1       0   248.4    .045       0  266.61      .1       0
Bank Sta=248.4,266.61
XS Rating Curve= 0 ,0
Exp/Cntr=0.3,0.1

Type RM Length L Ch R = 1 ,6841.3  ,401.4,397.1,392.7
XS GIS Cut Line= 3
      1832906.27      402138.136     1833117.207      401975.376
     1833177.103      401927.199
#Sta/Elev= 22
       0  839.59      19  826.24    28.6  819.81    38.1   814.7    47.6  812.45
    57.1   811.6   133.2  805.47   180.8  801.79   190.3  801.26   199.8  801.07
   209.3  800.67   219.3  799.59   228.4  798.91   237.9  799.58   247.4  802.71
   256.9   807.8   266.4  812.42     276  816.64   295.3   824.6   324.1  836.27
   333.7  840.34   343.3  844.83
#Mann= 3 , 0 , 0
       0      .1       0   219.3    .045       0   237.9      .1       0
Bank Sta=219.3,237.9
XS Rating Curve= 0 ,0
Exp/Cntr=0.3,0.1

Type RM Length L Ch R = 1 ,6444.3  ,520.7,518.7,516.5
XS GIS Cut Line= 3
      1833225.28       402440.22     1833398.457      402242.303
     1833457.051      402149.855
#Sta/Elev= 22
       0  864.75    29.2  846.23    58.4  827.82    77.9  815.57    87.7  809.55
    97.4  805.25   107.1  803.48   155.8  801.34   185.1   799.9   194.8  799.56
   204.5  799.36   214.3  798.31   223.7   796.4   233.8   795.3   238.7  796.38
   243.5  797.44   253.2  802.68     263  808.49   272.1  813.15   308.6  831.16
   345.1     849   372.4  862.44
#Mann= 3 , 0 , 0
       0      .1       0   223.7    .045       0   238.7      .1       0
Bank Sta=223.7,238.7
XS Rating Curve= 0 ,0
Exp/Cntr=0.3,0.1

Type RM Length L Ch R = 1 ,5925.6  ,275.3,282.2,289.1
XS GIS Cut Line= 3
     1833740.905      402731.886     1833777.363      402579.543
     1833902.363      402407.668
#Sta/Elev= 29
       0  828.31    19.6  822.25    29.4  819.49    39.2  817.07      49  815.38
    68.5  812.49    88.1   809.9   107.7  807.14   137.1  802.48   146.9  800.72
   156.6  799.35   185.6  796.44   195.3  795.62     205  795.25   214.6  795.06
   224.3  794.41   233.9  793.08   243.6   791.5   253.2  789.74   259.9   788.9
   262.9  788.53   272.6  788.74   274.9  789.48   282.2  791.84   291.9  798.79
   301.6  806.08   311.2   812.3   349.8  836.63   369.2  848.78
#Mann= 3 , 0 , 0
       0      .1       0   259.9    .045       0   274.9      .1       0
Bank Sta=259.9,274.9
XS Rating Curve= 0 ,0
Exp/Cntr=0.3,0.1

Type RM Length L Ch R = 1 ,5643.4  ,279.3,282.9,286.5
XS GIS Cut Line= 4
     1833859.395      402798.293     1834024.759       402690.22
     1834095.072      402638.136     1834143.249      402556.105
#Sta/Elev= 23
       0  812.47    18.8  808.84    75.3  798.33    84.7  796.65    94.1  795.58
   103.5  795.35   188.1  795.05   197.6  794.68   207.3  793.58   226.7  790.87
   245.5  788.09   255.9  787.31   265.6  788.15   275.3  792.48     285  798.97
   304.1  810.85   313.6  816.97   323.1  823.25   332.6  829.74   342.1  836.37
   361.2  850.02   370.7  857.06   380.2  864.32
#Mann= 3 , 0 , 0
       0      .1       0   245.5    .045       0   265.6      .1       0
Bank Sta=245.5,265.6
XS Rating Curve= 0 ,0
Exp/Cntr=0.3,0.1

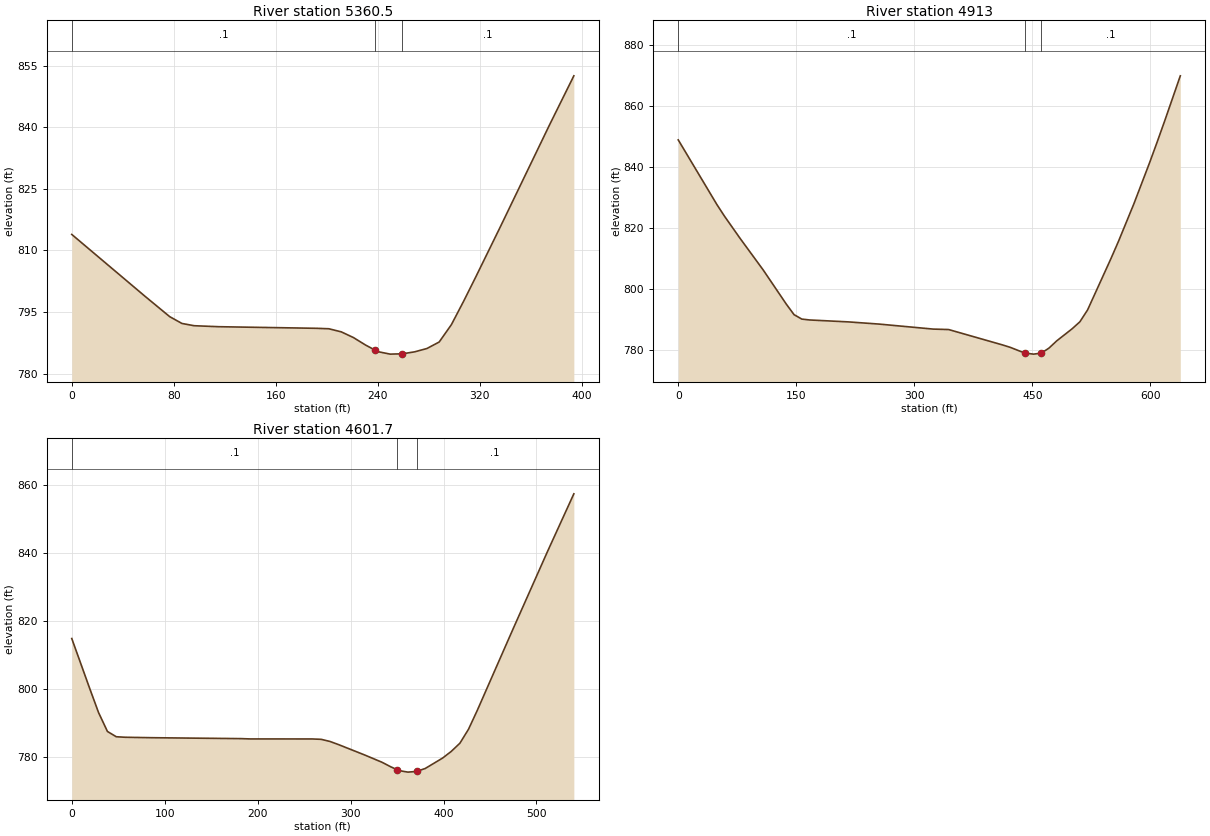
Type RM Length L Ch R = 1 ,5360.5  ,446.4,447.5,448.3
XS GIS Cut Line= 2
     1833985.697      403010.532     1834334.655      402828.241
#Sta/Elev= 24
       0  813.88    57.6  798.77    76.8  793.85    86.4  792.19      96  791.64
   115.2   791.4     192  791.01   201.6   790.9   211.3  790.15   220.9  788.75
   230.5  786.91   238.1  785.65   240.1  785.32   249.7  784.72   259.3   784.8
   268.9  785.28   278.5  786.09   288.1  787.67   297.7  791.91   307.3  797.62
   316.9  803.59   336.1  815.76   374.5  840.48   393.7  852.52
#Mann= 3 , 0 , 0
       0      .1       0   238.1    .045       0   259.3      .1       0
Bank Sta=238.1,259.3
XS Rating Curve= 0 ,0
Exp/Cntr=0.3,0.1

Type RM Length L Ch R = 1 ,4913    ,311.1,311.3,311.3
XS GIS Cut Line= 3
     1834058.613      403448.032     1834528.665      403225.376
      1834631.53      403168.084
#Sta/Elev= 30
       0  848.89    49.1   827.7    58.9  823.82    78.5  816.63     108  806.22
   137.4  795.01   147.2  791.58     157  790.14   166.8  789.85   215.9  789.22
   255.2   788.5   323.8  786.86   343.5  786.71   412.2  781.65     422  780.86
   440.2     779   451.4  778.65   461.2  778.97     471  780.62   480.9     783
   500.5  786.97   510.3  789.25   520.1  793.15   549.6  809.87   559.4  815.66
     579  827.99   598.6  841.22   608.4  848.12   618.2  855.22   637.9  869.89
#Mann= 3 , 0 , 0
       0      .1       0   440.2    .045       0   461.2      .1       0
Bank Sta=440.2,461.2
XS Rating Curve= 0 ,0
Exp/Cntr=0.3,0.1

Type RM Length L Ch R = 1 ,4601.7  ,477.4,470,462.6
XS GIS Cut Line= 4
     1834276.061       403690.22     1834516.947       403571.73
      1834669.29      403501.418     1834765.645      403462.355
#Sta/Elev= 29
       0  814.79    19.2   800.2    28.8  793.06    38.4  787.49    47.9  785.94
    57.5  785.79    86.3  785.66   182.2  785.39   191.8   785.3   258.9  785.29
   268.4  785.18   277.8  784.56   287.1  783.63   315.1  780.59   333.7  778.46
     343  777.14   350.1  776.26   352.3  775.99   361.7  775.55     371  775.76
   380.3  776.62     399  779.68   408.3  781.64   417.6  784.04   426.9  788.16
   436.2  793.62     474  817.11   511.8  840.31   540.2  857.29
#Mann= 3 , 0 , 0
       0      .1       0   350.1    .045       0     371      .1       0
Bank Sta=350.1,371
XS Rating Curve= 0 ,0
Exp/Cntr=0.3,0.1