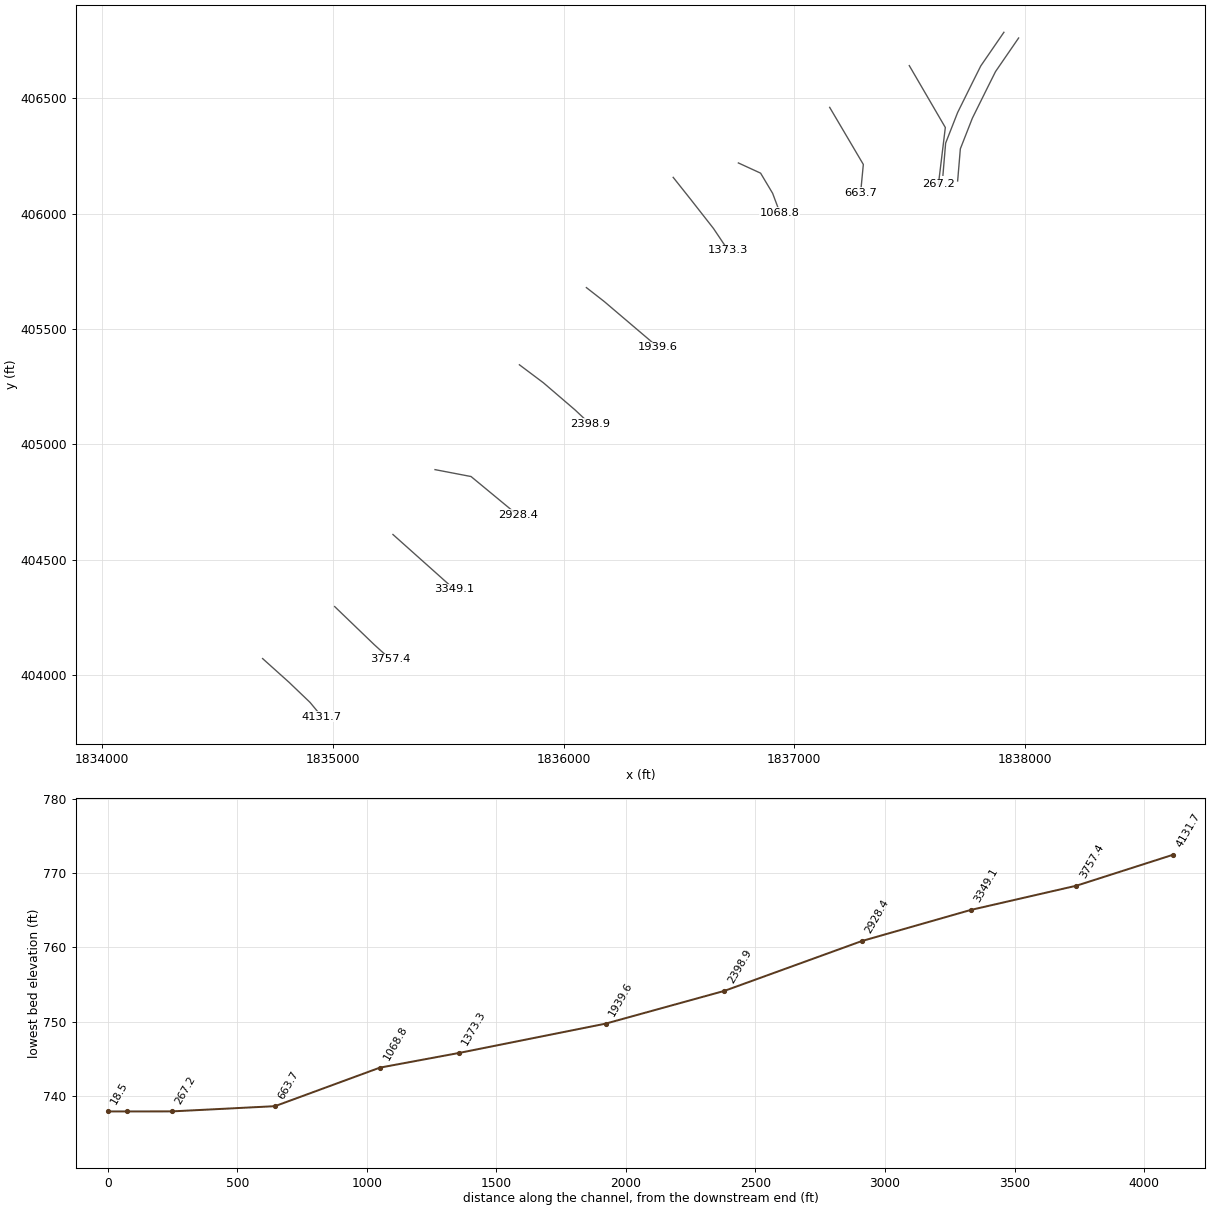
HEC-RAS study COALFORK.prj: COALFORK

--- COALFORK.g01 (geometry) --- (continued)

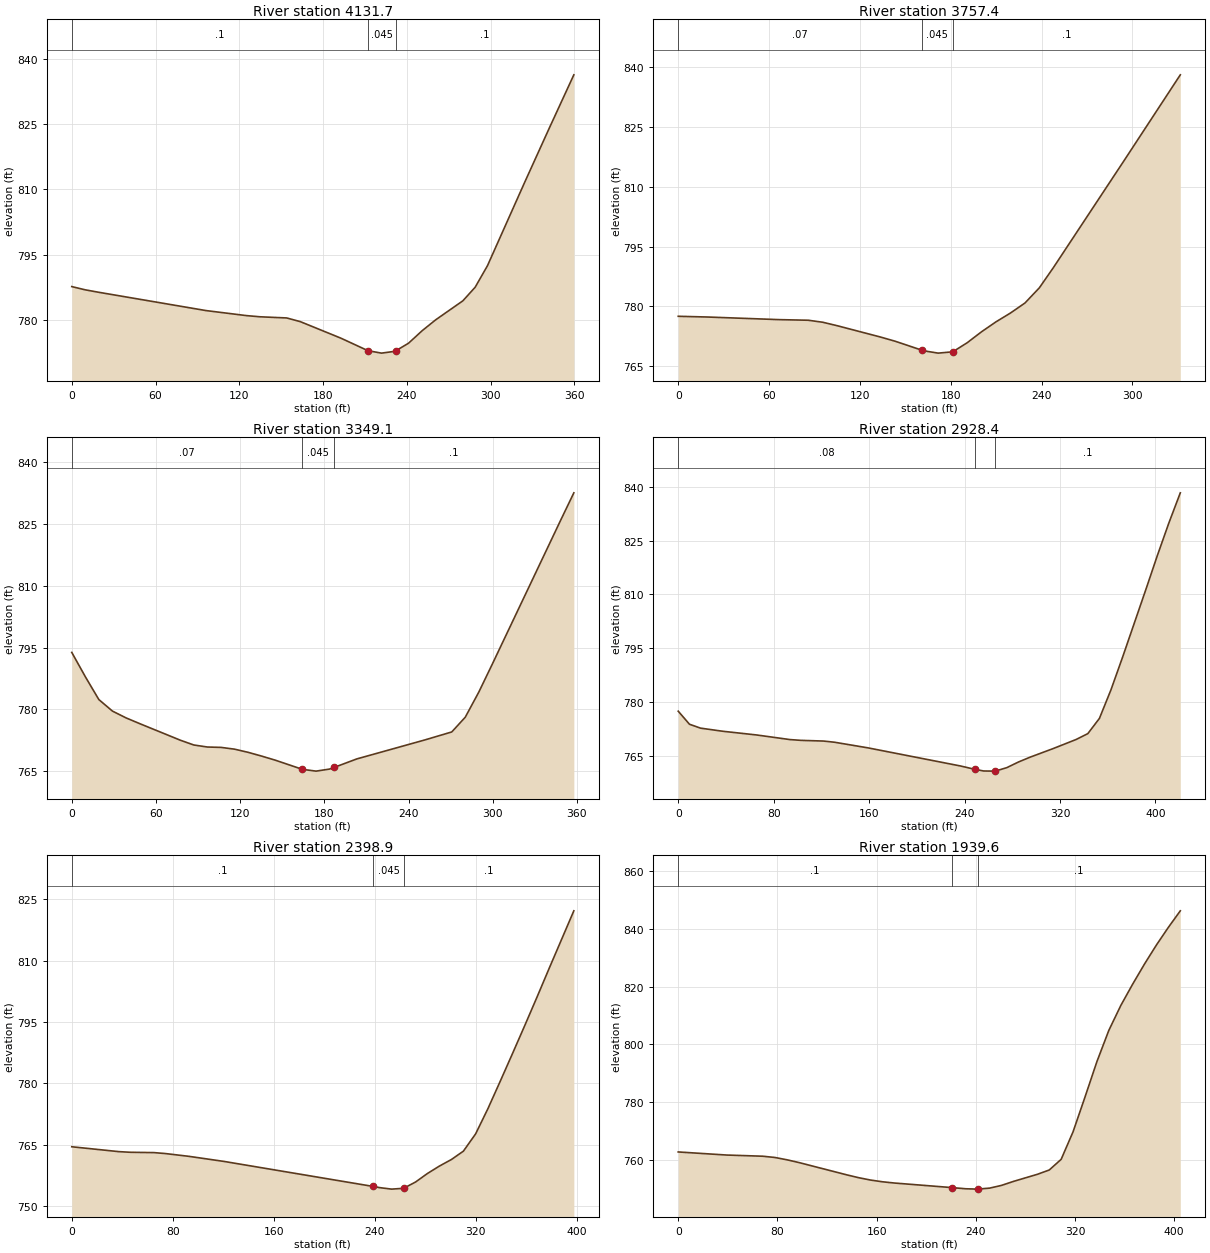
Type RM Length L Ch R = 1 ,4131.7  ,374.3,374.2,374.2
XS GIS Cut Line= 4
     1834695.332       404071.73     1834809.915      403968.866
     1834901.061      403881.626     1834951.842      403820.428
#Sta/Elev= 22
       0  787.73     9.6  786.99    19.2  786.43    96.2  782.23   125.1  781.08
   134.7  780.81     154  780.54   163.7   779.7   192.8  775.91   212.2  773.04
   221.9  772.48   231.6   772.9     232  772.98   241.3  774.76     251  777.61
   260.7  780.11   280.2  784.47     289  787.58   297.8   792.5   324.3   811.5
     342  823.97   359.7  836.26
#Mann= 3 , 0 , 0
       0      .1       0   212.2    .045       0     232      .1       0
Bank Sta=212.2,232
XS Rating Curve= 0 ,0
Exp/Cntr=0.3,0.1

Type RM Length L Ch R = 1 ,3757.4  ,407.4,408.3,409.1
XS GIS Cut Line= 3
     1835007.832      404296.991     1835179.707      404131.626
     1835248.717      404069.126
#Sta/Elev= 21
       0  777.53    19.1  777.35    66.8  776.69    85.9  776.54    95.4  776.04
   104.9  775.18   133.6  772.33   143.1   771.3   160.9  769.04   162.2  768.88
   171.7   768.3   181.3  768.63   190.8  770.89   200.4  773.67   209.9  776.15
   219.4  778.34     229  780.86   238.5  784.66   247.8  789.74   294.4   816.5
   331.6  838.03
#Mann= 3 , 0 , 0
       0     .07       0   160.9    .045       0   181.3      .1       0
Bank Sta=160.9,181.3
XS Rating Curve= 0 ,0
Exp/Cntr=0.3,0.1

Type RM Length L Ch R = 1 ,3349.1  ,419.6,420.7,421.3
XS GIS Cut Line= 2
     1835260.436      404609.491     1835527.363      404371.209
#Sta/Elev= 26
       0  793.85     9.7  787.92    19.3   782.4      29   779.6    38.7  777.95
    48.4  776.56    77.4  772.53      87  771.37    96.7  770.88   106.4  770.79
     116  770.36   125.7  769.59   135.4  768.67   145.1  767.68   164.4  765.46
   174.1  765.03   183.7  765.53   186.9  765.92   203.1  767.99   251.4  772.58
   270.8  774.54   280.4  778.11   290.1  784.23   299.8  791.08   348.1  825.71
   357.8  832.58
#Mann= 3 , 0 , 0
       0     .07       0   164.4    .045       0   186.9      .1       0
Bank Sta=164.4,186.9
XS Rating Curve= 0 ,0
Exp/Cntr=0.3,0.1

Type RM Length L Ch R = 1 ,2928.4  ,529.6,529.6,529.3
XS GIS Cut Line= 3
     1835442.728      404890.741     1835598.978      404860.793
     1835800.801      404694.126
#Sta/Elev= 27
       0  777.52     9.4  773.89    18.7   772.8    37.4  771.93    65.5  770.91
    93.6  769.62   102.9   769.4   121.7  769.21     131  768.88   159.1  767.31
   236.6  762.27   248.6  761.34     256  760.88   265.7  760.84   275.4  761.81
   285.1  763.37   294.8  764.71   314.2  767.11   333.6  769.66   343.3  771.28
     353  775.51   362.7  783.48   372.4  792.53   391.8  811.25   401.4  820.68
   411.1  829.79   420.8  838.28
#Mann= 3 , 0 , 0
       0     .08       0   248.6    .045       0   265.7      .1       0
Bank Sta=248.6,265.7
XS Rating Curve= 0 ,0
Exp/Cntr=0.3,0.1

Type RM Length L Ch R = 1 ,2398.9  ,459.9,459.2,458.8
XS GIS Cut Line= 4
     1835808.613      405345.168      1835912.78      405267.043
     1836049.499      405149.855     1836113.301      405089.959
#Sta/Elev= 24
       0   764.5    37.2  763.31    46.5  763.15    65.1  763.07    74.4  762.83
      93  762.15   120.9   760.9   238.9  754.79   243.9  754.51   253.4  754.14
   262.9  754.34   272.4  755.88   281.8  757.96   291.3  759.78   300.8  761.38
   310.3  763.43     320  767.66   329.7   773.8   339.4  780.46   349.2  787.29
   358.9  794.13   368.6  801.08   378.3  808.16   397.8  822.19
#Mann= 3 , 0 , 0
       0      .1       0   238.9    .045       0   262.9      .1       0
Bank Sta=238.9,262.9
XS Rating Curve= 0 ,0
Exp/Cntr=0.3,0.1

Type RM Length L Ch R = 1 ,1939.6  ,570.4,566.4,561.9
XS GIS Cut Line= 3
     1836098.978      405679.803     1836175.801      405619.907
     1836410.176      405420.688
#Sta/Elev= 30
       0  762.62      39  761.55    68.2  761.14    77.9  760.71    87.7   759.9
    97.4  758.94   135.9  754.68   145.5  753.69   155.1  752.87   164.7  752.27
   174.3  751.84   220.8  750.25     232  749.84   241.6  749.72   251.2  750.07
   260.8  751.02   270.4   752.4   289.7  754.86   299.3  756.36   308.9  760.07
   318.5  769.63   328.1  781.65   337.7  793.94   347.3  804.77     357  813.45
   366.6  820.88   376.2   827.9   385.8  834.48   395.4  840.58     405   846.3
#Mann= 3 , 0 , 0
       0      .1       0   220.8    .045       0   241.6      .1       0
Bank Sta=220.8,241.6
XS Rating Curve= 0 ,0
Exp/Cntr=0.3,0.1

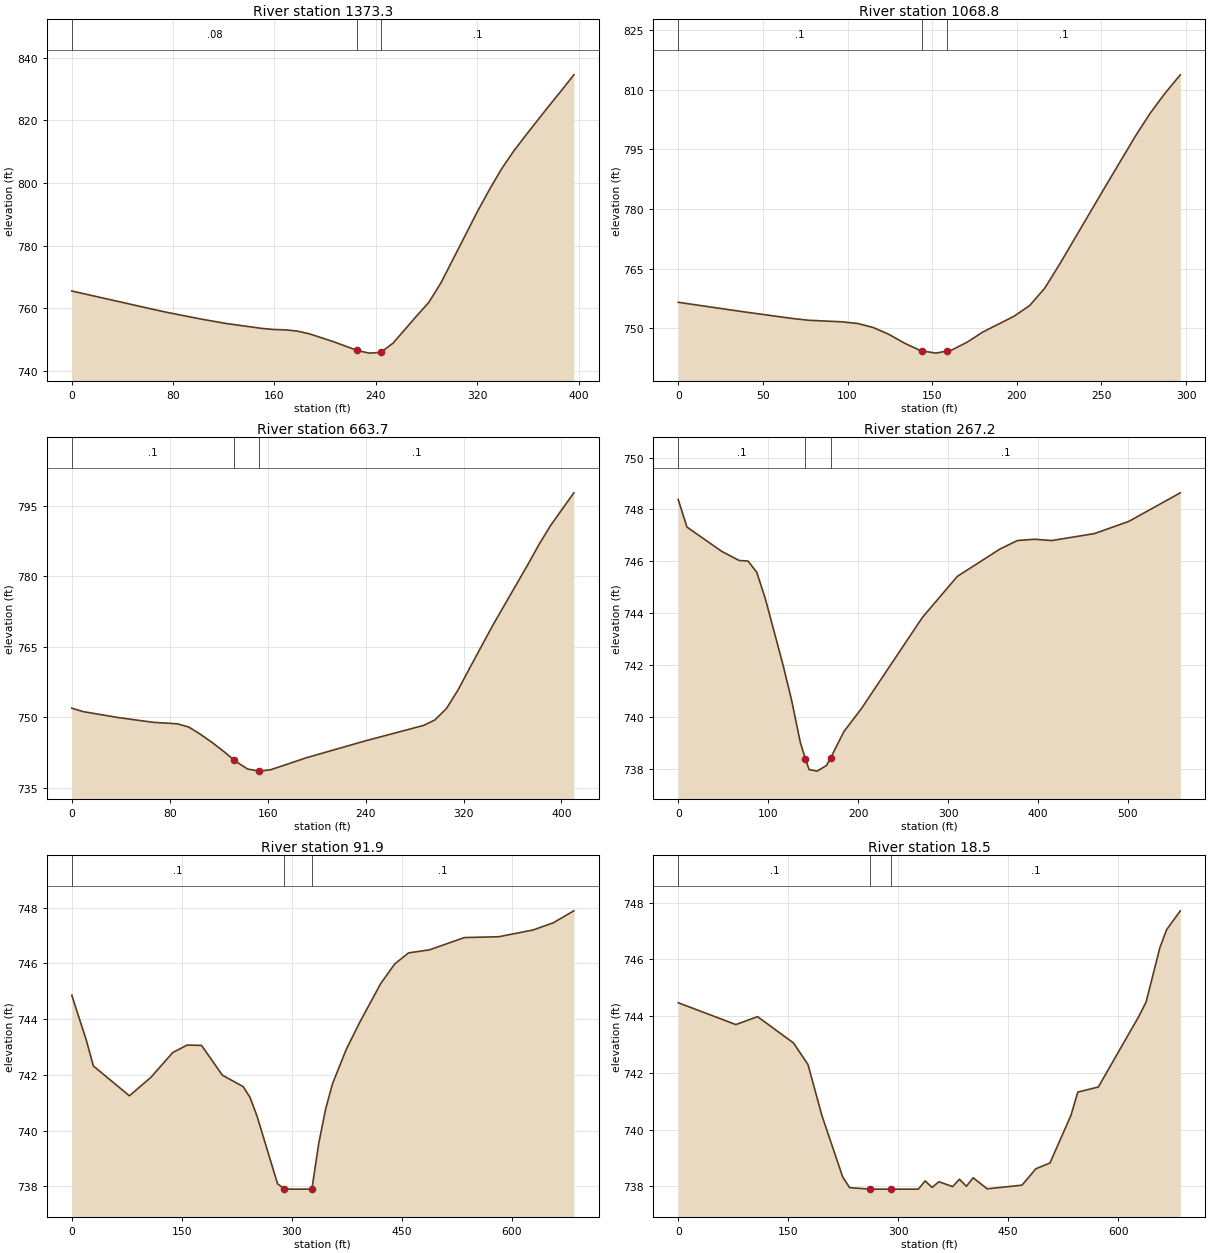
Type RM Length L Ch R = 1 ,1373.3  ,307.4,304.5,301.7
XS GIS Cut Line= 4
      1836475.28      406157.668     1836550.801      406062.616
     1836649.759      405936.313     1836713.561      405841.261
#Sta/Elev= 26
       0  765.58    65.4  759.62    74.7  758.81   102.7  756.58   121.4  755.25
   149.7  753.67   159.2  753.31   168.6  753.19     178   752.8   187.5  751.93
   206.4  749.44   225.2  746.65   234.7  745.77   243.9     746   253.5  748.91
   272.4   757.7   281.8  761.93   291.4  768.17     320  790.76   329.6  797.84
   339.1   804.4   348.6  810.06   358.2  815.14   377.2  824.86   386.8  829.65
   396.3   834.5
#Mann= 3 , 0 , 0
       0     .08       0   225.2    .045       0   243.9      .1       0
Bank Sta=225.2,243.9
XS Rating Curve= 0 ,0
Exp/Cntr=0.3,0.1

Type RM Length L Ch R = 1 ,1068.8  ,405.1,405.1,404.8
XS GIS Cut Line= 4
     1836757.832      406220.168     1836854.186      406175.897
      1836906.27      406088.657      1836937.52      406005.324
#Sta/Elev= 25
       0  756.57    38.6  754.18    67.5   752.5    77.1  752.05    96.4  751.67
     106  751.25   115.3  750.22   124.5   748.5   133.8  746.28     143  744.45
   143.8  744.39   152.2   743.8   158.8  744.34   161.5  744.56   170.7  746.55
   179.9  749.09   198.4  753.07   207.6  755.75   216.5   760.1   225.4   766.2
   252.1  785.49   269.9  798.18   278.8  804.06   287.7  809.14   296.6   813.7
#Mann= 3 , 0 , 0
       0      .1       0   143.8    .045       0   158.8      .1       0
Bank Sta=143.8,158.8
XS Rating Curve= 0 ,0
Exp/Cntr=0.3,0.1

Type RM Length L Ch R = 1 ,663.7   ,396.5,396.5,396.8
XS GIS Cut Line= 3
     1837153.665      406461.053     1837299.499      406213.657
      1837287.78      406091.261
#Sta/Elev= 26
       0  751.97     9.6  751.23    38.3  749.97      67  748.96    86.2  748.66
    95.7  747.96   105.3   746.4   114.9  744.64   124.4  742.74   132.5  740.98
     134  740.66   143.6  739.06   153.2  738.61   162.7  738.92   191.4  741.43
   239.3     745   287.2   748.3   296.6  749.47   306.1  751.92   315.6  755.88
     325  760.48   343.9  769.57   372.3  782.36   381.8   786.8   391.2   790.8
   410.1   797.7
#Mann= 3 , 0 , 0
       0      .1       0   132.5    .045       0   153.2      .1       0
Bank Sta=132.5,153.2
XS Rating Curve= 0 ,0
Exp/Cntr=0.3,0.1

Type RM Length L Ch R = 1 ,267.2   ,197.9,175.3,152
XS GIS Cut Line= 3
     1837498.717      406642.043     1837654.967      406373.813
      1837625.02       406127.72
#Sta/Elev= 26
       0  748.38     9.7  747.32    48.5  746.38    67.9  746.03    77.6  746.01
    87.3  745.58      97  744.54   116.4  742.02   126.1  740.64   135.8  739.01
  141.36  738.39   145.5  737.97   154.5  737.91   164.9  738.13   169.5  738.42
   184.3  739.44   203.7  740.32   271.6  743.84   310.4  745.42   358.1  746.48
   377.2   746.8   396.2  746.85   415.3   746.8     463  747.07   501.1  747.54
   558.3  748.64
#Mann= 3 , 0 , 0
       0      .1       0  141.36    .045       0   169.5      .1       0
Bank Sta=141.36,169.5
XS Rating Curve= 0 ,0
Exp/Cntr=0.3,0.1

Type RM Length L Ch R = 1 ,91.9    ,73.4,73.4,73.4
XS GIS Cut Line= 6
     1837908.874      406786.574     1837808.613      406640.741
     1837774.759      406573.032     1837708.353      406438.918
      1837656.27      406306.105     1837644.551      406166.782
#Sta/Elev= 30
       0  744.86    19.7  743.26    29.5  742.32    78.6  741.25   108.2  741.92
   137.6   742.8   157.3  743.07     177  743.06   205.4  741.99   233.8  741.58
   243.2  741.19   252.7  740.52   280.7  738.09   290.1  737.91   299.4   737.9
   327.5   737.9   336.8  739.53   346.2  740.77   355.6  741.68   374.3  742.91
     393   743.9   421.4  745.28   440.4  745.98   459.4  746.38   487.9  746.49
   535.5  746.93   582.3  746.96   628.9   747.2   656.8  747.46   684.8  747.89
#Mann= 3 , 0 , 0
       0      .1       0   290.1    .045       0   327.5      .1       0
Bank Sta=290.1,327.5
XS Rating Curve= 0 ,0
Exp/Cntr=0.3,0.1

Type RM Length L Ch R = 1 ,18.5    ,9.4,18.5,27.5
XS GIS Cut Line= 6
     1837972.676      406761.834     1837872.415      406616.001
     1837838.561      406548.293     1837772.155      406414.178
     1837720.072      406281.366     1837708.353      406142.043
#Sta/Elev= 30
       0  744.47    78.6   743.7   108.2  743.98   157.3  743.05     177  742.29
   195.9   740.5   224.3  738.33   233.8  737.95     262   737.9   290.1   737.9
   327.5   737.9   336.8  738.19   346.2  737.96   355.6  738.16   374.3  737.99
   383.6  738.25     393     738   402.3   738.3   421.4  737.91   468.9  738.04
   487.9  738.62     507  738.82   535.5  740.49     545  741.32     573   741.5
   628.9  744.02   638.2   744.5   656.8   746.4   666.2  747.05   684.8  747.71
#Mann= 3 , 0 , 0
       0      .1       0     262    .045       0   290.1      .1       0
Bank Sta=262,290.1
XS Rating Curve= 0 ,0
Exp/Cntr=0.3,0.1

Chan Stop Cuts=-1
Use User Specified Reach Order=0
Composite Channel Slope=5